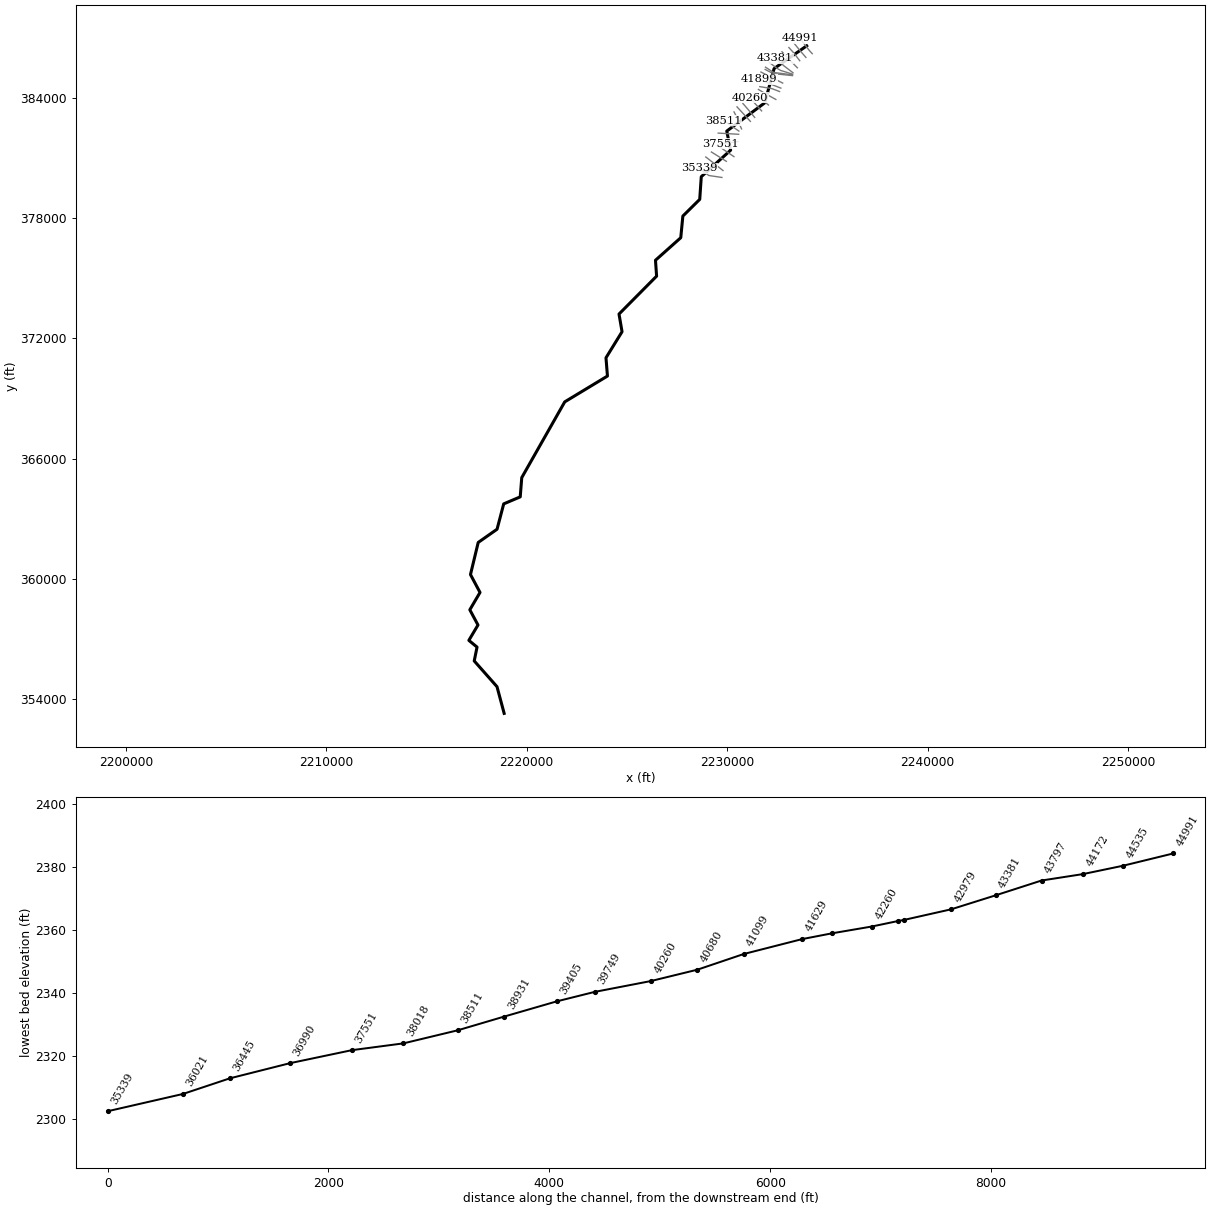
--- NFANTNYCK.prj (project) ---

Proj Title=NFANTNYCK
Current Plan=p01
Default Exp/Contr=0.3,0.1
English Units
Geom File=g01
Flow File=f01
Plan File=p01
Y Axis Title=Elevation
X Axis Title(PF)=Main Channel Distance
X Axis Title(XS)=Station
BEGIN DESCRIPTION:
Stream Name- North Fork Anthony Creek
Flood Zone: Zone A
Greenbrier County, WV
County-Wide Study
WVDHSEM-2018-3, Flood Risk Project
HEC-RAS Version: 5.0.7
General Notes:
For the Hydrology Regression was used.
END DESCRIPTION:
DSS Export Rating Curves= 0
DSS Export Rating Curve Sorted= 0
DSS Export Volume Flow Curves= 0
DXF Filename=A2c.
DXF OffsetX= 0
DXF OffsetY= 0
DXF ScaleX= 1
DXF ScaleY= 10

--- NFANTNYCK.p01 (plan) ---

Plan Title=Floodplain
Program Version=5.07
Short Identifier=Floodplain
Geom File=g01
Flow File=f01
Subcritical Flow
K Sum by GR= 0
Std Step Tol= 0.01
Critical Tol= 0.01
Num of Std Step Trials= 20
Max Error Tol= 0.3
Flow Tol Ratio= 0.001
Split Flow NTrial= 30
Split Flow Tol= 0.02
Split Flow Ratio= 0.02
Log Output Level= 0
Friction Slope Method= 1
Unsteady Friction Slope Method= 2
Unsteady Bridges Friction Slope Method= 1
Parabolic Critical Depth
Global Vel Dist= 0 , 0 , 0
Global Log Level= 0
CheckData=True
Encroach Param=-1 ,0,0, 0
Computation Interval=1MIN
Output Interval=1HOUR
Instantaneous Interval=1HOUR
Mapping Interval=1HOUR
Computation Time Step Use Courant=        0
Computation Time Step Use Time Series=    0
Computation Time Step Count To Double=0
Computation Time Step Max Doubling=0
Computation Time Step Max Halving=0
Computation Time Step Residence Courant=0
Run HTab= 0
Run UNet= 0
Run Sediment= 0
Run PostProcess= 0
Run WQNet= 0
Run RASMapper= 0
UNET Theta= 1
UNET Theta Warmup= 1
UNET ZTol= 0.02
UNET ZSATol= 0.02
UNET MxIter= 20
UNET Max Iter WO Improvement= 0
UNET MaxInSteps= 0
UNET DtIC= 0
UNET DtMin= 0
UNET MaxCRTS= 20
UNET WFStab= 2
UNET SFStab= 1
UNET WFX= 1
UNET SFX= 1
UNET 1D Methodology=Finite Difference
UNET DSS MLevel= 4
UNET Pardiso=0
UNET DZMax Abort= 100
UNET Use Existing IB Tables=-1
UNET Froude Reduction=False
UNET Froude Limit= 0.8
UNET Froude Power= 4
UNET D1 Cores= 0
UNET D2 Coriolis=0
UNET D2 Cores= 0
UNET D2 Theta= 1
UNET D2 Theta Warmup= 1
UNET D2 Z Tol= 0.01
UNET D2 Volume Tol= 0.01
UNET D2 Max Iterations= 20
UNET D2 Equation= 0
UNET D2 RampUpFraction=0.1
UNET D2 TimeSlices= 1
UNET D2 BCVolumeCheck=0
UNET D1D2 MaxIter= 0
UNET D1D2 ZTol=0.01
UNET D1D2 QTol=0.1
UNET D1D2 MinQTol=1
Write IC File= 0
Write IC File at Fixed DateTime=0
Write IC File at Sim End=0
Echo Input=False
Echo Parameters=False
Echo Output=False
Write Detailed= 0
HDF Write Warmup=0
HDF Write Time Slices=0
HDF Flush=0
HDF Face Node Velocities=0
HDF Compression= 1
HDF Chunk Size= 1
HDF Spatial Parts= 1
HDF Use Max Rows=0
HDF Fixed Rows= 1
Calibration Method= 0
Calibration Iterations= 20
Calibration Max Change=0.05
Calibration Tolerance=0.2
Calibration Maximum=1.5
Calibration Minimum=0.5
Calibration Optimization Method= 1
WQ AD Non Conservative
WQ ULTIMATE=-1
WQ Max Comp Step=1HOUR
WQ Output Interval=15MIN
WQ Output Selected Increments= 0
WQ Output face flow=0
WQ Output face velocity=0
WQ Output face area=0
WQ Output face dispersion=0
WQ Output cell volume=0
WQ Output cell surface area=0
WQ Output cell continuity=0
WQ Output cumulative cell continuity=0
WQ Output face conc=0
WQ Output face dconc_dx=0
WQ Output face courant=0
WQ Output face peclet=0
WQ Output face adv mass=0
WQ Output face disp mass=0
WQ Output cell mass=0
WQ Output cell source sink temp=0
WQ Output nsm pathways=0
WQ Output nsm derived pathways=0
WQ Output MaxMinRange=-1
WQ Daily Max Min Mean=-1
WQ Daily Range=0
WQ Daily Time=0
WQ Create Restart=0
WQ Fixed Restart=0
WQ System Summary=0
WQ Write To DSS=0
WQ Use Fixed Temperature=0
Sorting and Armoring Iterations= 10
XS Update Threshold= 0.02
Bed Roughness Predictor= 0
Hydraulics Update Threshold= 0.02
Energy Slope Method= 1
Volume Change Method= 1
Sediment Retention Method= 0
XS Weighting Method= 0
Number of US Weighted Cross Sections= 1
Number of DS Weighted Cross Sections= 1
Upstream XS Weight=0
Main XS Weight=1
Downstream XS Weight=0
Number of DS XS's Weighted with US Boundary= 1
Upstream Boundary Weight= 1
Weight of XSs Associated with US Boundary= 0
Number of US XS's Weighted with DS Boundary= 1
Downstream Boundary Weight= 0.5
Weight of XSs Associated with DS Boundary= 0.5
Percentile Method= 0
Sediment Output Level= 3
Mass or Volume Output= 0
Output Increment Type= 1
Profile and TS Output Increment= 1
XS Output Flag= 0
XS Output Increment= 10
Write Gradation File= 0
Read Gradation Hotstart= 0
Write HDF5 File= 1
Write Binary Output= 1
Write DSS Sediment File= 0
SV Curve= 0
Specific Gage Flag= 0

--- NFANTNYCK.f01 (steady flow) ---

Flow Title=Flow
Program Version=5.07
Number of Profiles= 6
Profile Names=f1p,f10p,f4p,f2p,f02p,f1pplus
River Rch & RM=LAURELRN2,Main            ,16185
     488     256     342     413     684     722
River Rch & RM=LAURELRN2,Main            ,15475
     566     299     398     479     791     838
River Rch & RM=LAURELRN2,Main            ,13512
     655     348     462     555     913     969
River Rch & RM=LAURELRN2,Main            ,11607
     732     390     517     621    1020    1080
River Rch & RM=LAURELRN2,Main            ,8528
     852     457     604     724    1180    1260
River Rch & RM=LAURELRN2,Main            ,6084
     949     511     674     807    1310    1400
River Rch & RM=LAURELRN2,Main            ,2993
    1060     571     751     899    1460    1560
River Rch & RM=MEADOWCK1,Main            ,75581
     529     279     371     448     740     782
River Rch & RM=MEADOWCK1,Main            ,73978
     598     316     420     506     834     884
River Rch & RM=MEADOWCK1,Main            ,71430
     678     361     478     575     945    1000
River Rch & RM=MEADOWCK1,Main            ,69203
     792     424     560     672    1100    1170
River Rch & RM=MEADOWCK1,Main            ,67339
     882     474     625     749    1220    1300
River Rch & RM=MEADOWCK1,Main            ,64109
    1010     548     721     863    1400    1500
River Rch & RM=MEADOWCK1,Main            ,61239
    1140     619     812     971    1570    1690
River Rch & RM=MEADOWCK1,Main            ,59576
    1280     700     917    1090    1770    1900
River Rch & RM=MEADOWCK1,Main            ,56054
    1450     794    1040    1240    1990    2140
River Rch & RM=MEADOWCK1,Main            ,50980
    1720     950    1240    1470    2360    2550
River Rch & RM=MEADOWCK1,Main            ,44209
    1940    1080    1400    1660    2650    2870
River Rch & RM=MEADOWCK1,Main            ,42625
    1840    1020    1320    1570    2510    2720
River Rch & RM=MEADOWCK1,Main            ,38864
    2190    1220    1580    1870    2980    3230
River Rch & RM=MEADOWCK1,Main            ,31946
    2500    1400    1810    2140    3390    3690
River Rch & RM=MEADOWCK1,Main            ,24140
    2780    1560    2020    2390    3780    4120
River Rch & RM=MEADOWCK1,Main            ,14473
    3730    2120    2720    3210    5030    5510
River Rch & RM=MFANTNYCK,Main            ,62239
    1310     714     935    1120    1800    1940
River Rch & RM=MFANTNYCK,Main            ,61636
    1410     772    1010    1200    1940    2090
River Rch & RM=MFANTNYCK,Main            ,58106
    1580     868    1130    1350    2160    2330
River Rch & RM=MFANTNYCK,Main            ,55360
    1820    1010    1310    1560    2490    2690
River Rch & RM=MFANTNYCK,Main            ,52938
    2030    1120    1460    1730    2760    3000
River Rch & RM=MFANTNYCK,Main            ,48015
    2310    1290    1670    1980    3150    3420
River Rch & RM=MFANTNYCK,Main            ,44550
    2730    1530    1980    2340    3700    4030
River Rch & RM=MFANTNYCK,Main            ,38407
    3100    1750    2250    2660    4200    4590
River Rch & RM=MFANTNYCK,Main            ,29623
    3460    1960    2520    2980    4680    5120
River Rch & RM=MFANTNYCK,Main            ,25319
    3880    2210    2840    3340    5230    5740
River Rch & RM=MFANTNYCK,Main            ,16951
    4320    2470    3160    3720    5810    6390
River Rch & RM=MFANTNYCK,Main            ,12276
    4850    2780    3560    4180    6510    7170
River Rch & RM=NFANTNYCK,Main            ,44991
    1410     771    1010    1200    1940    2080
River Rch & RM=NFANTNYCK,Main            ,42260
    1650     907    1180    1410    2260    2440
River Rch & RM=NFANTNYCK,Main            ,38018
    1880    1040    1360    1610    2570    2790
River Rch & RM=NFANTNYCK,Main            ,34796
    2230    1240    1610    1910    3040    3300
River Rch & RM=NFANTNYCK,Main            ,29090
    2490    1390    1800    2140    3390    3680
River Rch & RM=NFANTNYCK,Main            ,20166
    2840    1590    2060    2430    3840    4190
River Rch & RM=NFANTNYCK,Main            ,11738
    3200    1810    2330    2750    4330    4740
River Rch & RM=NFANTNYCK,Main            ,8976
    3560    2020    2600    3060    4810    5270
River Rch & RM=TWOMILERN,Main            ,1186
     601     318     423     509     838     889
Boundary for River Rch & Prof#=LAURELRN2,Main            , 1
Up Type= 0
Dn Type= 3
Dn Slope=0.035124
Boundary for River Rch & Prof#=LAURELRN2,Main            , 2
Up Type= 0
Dn Type= 3
Dn Slope=0.035124
Boundary for River Rch & Prof#=LAURELRN2,Main            , 3
Up Type= 0
Dn Type= 3
Dn Slope=0.035124
Boundary for River Rch & Prof#=LAURELRN2,Main            , 4
Up Type= 0
Dn Type= 3
Dn Slope=0.035124
Boundary for River Rch & Prof#=LAURELRN2,Main            , 5
Up Type= 0
Dn Type= 3
Dn Slope=0.035124
Boundary for River Rch & Prof#=LAURELRN2,Main            , 6
Up Type= 0
Dn Type= 3
Dn Slope=0.035124
Boundary for River Rch & Prof#=MEADOWCK1,Main            , 1
Up Type= 0
Dn Type= 3
Dn Slope=0.011297
Boundary for River Rch & Prof#=MEADOWCK1,Main            , 2
Up Type= 0
Dn Type= 3
Dn Slope=0.011297
Boundary for River Rch & Prof#=MEADOWCK1,Main            , 3
Up Type= 0
Dn Type= 3
Dn Slope=0.011297
Boundary for River Rch & Prof#=MEADOWCK1,Main            , 4
Up Type= 0
Dn Type= 3
Dn Slope=0.011297
Boundary for River Rch & Prof#=MEADOWCK1,Main            , 5
Up Type= 0
Dn Type= 3
Dn Slope=0.011297
Boundary for River Rch & Prof#=MEADOWCK1,Main            , 6
Up Type= 0
Dn Type= 3
Dn Slope=0.011297
Boundary for River Rch & Prof#=MFANTNYCK,Main            , 1
Up Type= 0
Dn Type= 3
Dn Slope=0.001473
Boundary for River Rch & Prof#=MFANTNYCK,Main            , 2
Up Type= 0
Dn Type= 3
Dn Slope=0.001473
Boundary for River Rch & Prof#=MFANTNYCK,Main            , 3
Up Type= 0
Dn Type= 3
Dn Slope=0.001473
Boundary for River Rch & Prof#=MFANTNYCK,Main            , 4
Up Type= 0
Dn Type= 3
Dn Slope=0.001473
Boundary for River Rch & Prof#=MFANTNYCK,Main            , 5
Up Type= 0
Dn Type= 3
Dn Slope=0.001473
Boundary for River Rch & Prof#=MFANTNYCK,Main            , 6
Up Type= 0
Dn Type= 3
Dn Slope=0.001473
Boundary for River Rch & Prof#=NFANTNYCK,Main            , 1
Up Type= 0
Dn Type= 3
Dn Slope=0.006644
Boundary for River Rch & Prof#=NFANTNYCK,Main            , 2
Up Type= 0
Dn Type= 3
Dn Slope=0.006644
Boundary for River Rch & Prof#=NFANTNYCK,Main            , 3
Up Type= 0
Dn Type= 3
Dn Slope=0.006644
Boundary for River Rch & Prof#=NFANTNYCK,Main            , 4
Up Type= 0
Dn Type= 3
Dn Slope=0.006644
Boundary for River Rch & Prof#=NFANTNYCK,Main            , 5
Up Type= 0
Dn Type= 3
Dn Slope=0.006644
Boundary for River Rch & Prof#=NFANTNYCK,Main            , 6
Up Type= 0
Dn Type= 3
Dn Slope=0.006644
Boundary for River Rch & Prof#=TWOMILERN,Main            , 1
Up Type= 0
Dn Type= 3
Dn Slope=0.021324
Boundary for River Rch & Prof#=TWOMILERN,Main            , 2
Up Type= 0
Dn Type= 3
Dn Slope=0.021324
Boundary for River Rch & Prof#=TWOMILERN,Main            , 3
Up Type= 0
Dn Type= 3
Dn Slope=0.021324
Boundary for River Rch & Prof#=TWOMILERN,Main            , 4
Up Type= 0
Dn Type= 3
Dn Slope=0.021324
Boundary for River Rch & Prof#=TWOMILERN,Main            , 5
Up Type= 0
Dn Type= 3
Dn Slope=0.021324
Boundary for River Rch & Prof#=TWOMILERN,Main            , 6
Up Type= 0
Dn Type= 3
Dn Slope=0.021324
DSS Import GetInterval= 0
DSS Import GetPeak= 0
DSS Import FillOption= 0

--- NFANTNYCK.g01 (geometry) ---

Geom Title=Geometry
Program Version=5.07

River Reach=NFANTNYCK       ,Main
Reach XY= 30
2233966.81314497386605.0877447282232340.77768314385470.936469734
 2231877.3383213383761.7072766422229979.76862563382348.512924567
2230171.60912122 381395.387862312228708.06742889380072.471216813
2228630.81036556378940.5269583912227788.79662964378107.193651304
2227684.62984322377026.4641854762226423.34496422375901.464466974
2226478.90062739375107.1934177282224603.90076847373215.700481564
2224754.94246113 372332.019834222223953.72720006371031.672697395
2224026.64372088370120.2142184822221895.56727439368831.151835978
2219751.47018464365049.9018525632219675.08122981364088.096361473
2218851.29646005363739.1380698982218518.83124572362472.644867972
2217578.72715481 361812.922762232217193.31027472360210.492240056
2217669.00486138359317.263055399 2217160.3244483358451.811702311
2217567.44240047357691.3949160582217111.71332505356924.901698396
2217520.32984808 356588.969064182217380.38142289355898.259722814
2218516.22692022354613.2698387212218873.18224305353280.180313304

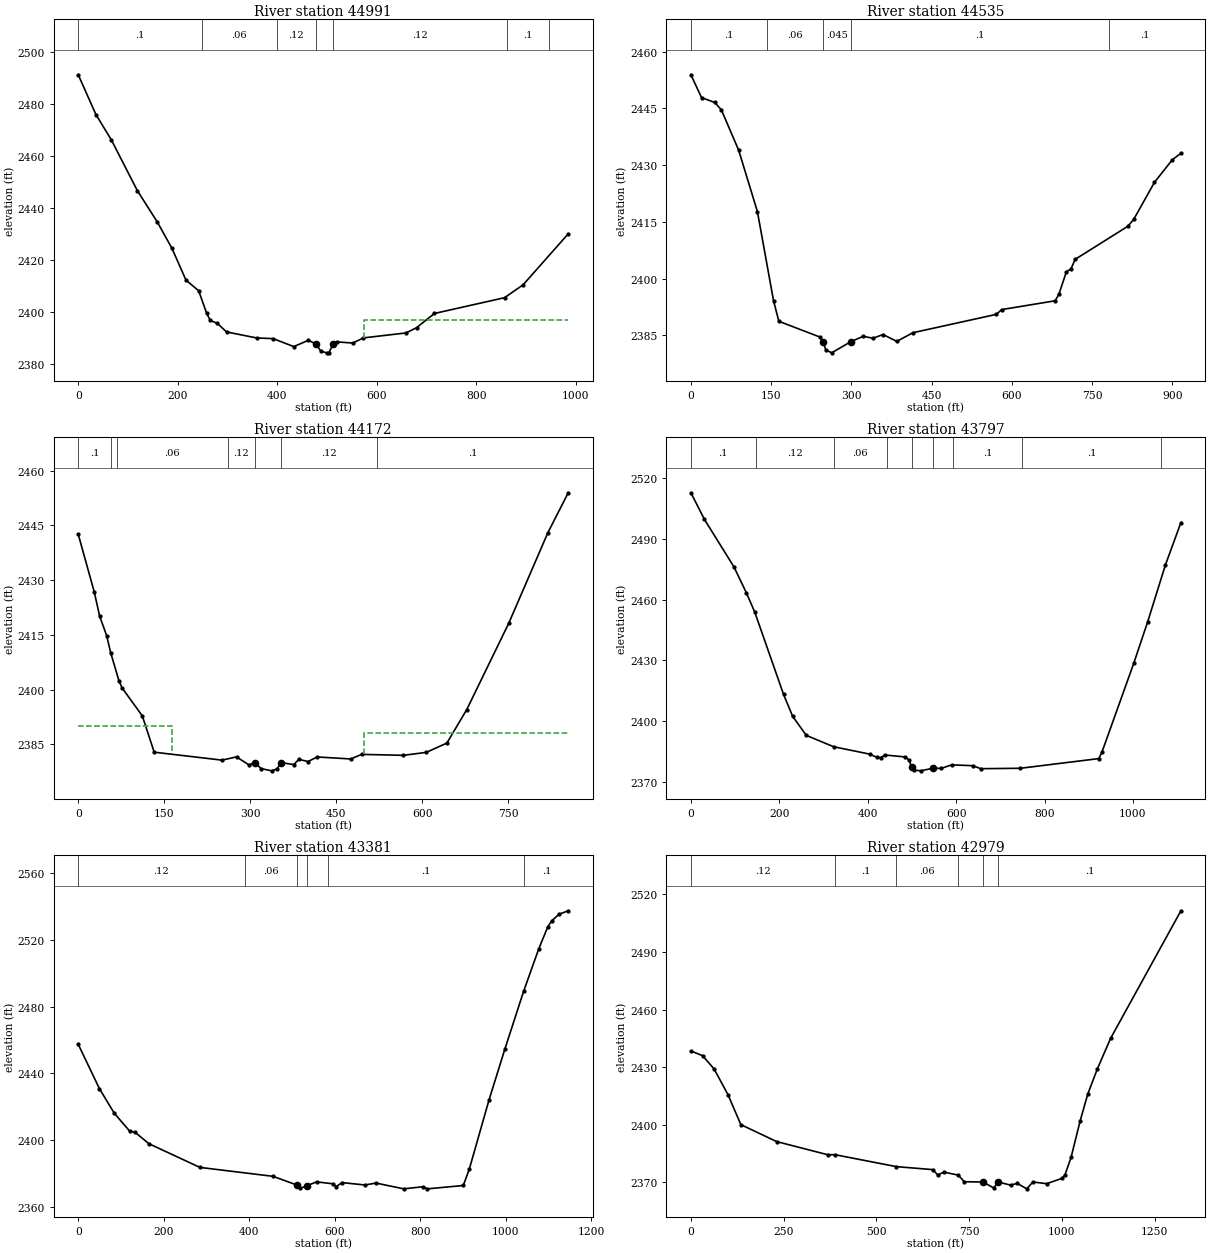
Type RM Length L Ch R = 1 ,44991   ,450,455.8,442.1
XS GIS Cut Line= 3
2234243.94054347386212.980589315 2234092.8988508386380.688915312
2233626.99492697 386980.03548564
#Sta/Elev= 30
       0 2491.25    35.6 2475.94    66.5 2466.23   118.7 2446.72   159.2 2434.54
   188.4 2424.46   216.6 2412.25   242.1 2408.18   257.8 2399.64   265.3 2396.75
   279.5 2395.64     298 2392.33   358.8 2390.01   391.7 2389.76   433.2 2386.69
   462.3  2389.1   478.1  2387.7   487.6  2384.9   499.7 2384.29   503.9 2384.41
   512.2 2387.54   519.7  2388.5   551.8 2388.06   573.2 2390.04   658.7 2391.94
   680.1 2393.98   715.8 2399.43   856.8  2405.5   894.2 2410.48   984.8 2430.08
#Mann= 7 ,-1 , 0
       0      .1       0  248.95     .06       0  398.64     .12       0
   478.1    .045       0   512.2     .12       0  861.91      .1       0
  946.87      .1       0
#XS Ineff= 2 , 0
                          573.57         2396.97
Permanent Ineff=
       F       F
Bank Sta=478.1,512.2
XS Rating Curve= 0 ,0
Exp/Cntr=0.3,0.1

Type RM Length L Ch R = 1 ,44535   ,357.3,363.6,350.9
XS GIS Cut Line= 3
2233928.31551856386027.5639653952233648.10708947386350.480642393
 2233341.8570458386730.688871473
#Sta/Elev= 30
       0 2453.91    19.9 2447.87    44.2 2446.61    56.8 2444.68    89.3 2433.95
   124.3 2417.73   154.5 2394.11   164.4 2388.72   241.4 2384.54  246.932383.235
   252.1 2381.19   263.1 2380.38   298.7 2383.32   321.9 2384.74   340.5 2384.25
   359.1 2385.22   384.8 2383.41   414.9  2385.7     571 2390.56   580.6 2391.81
   680.9 2394.15   687.9 2395.94   701.7 2401.79   710.4 2402.62   718.2 2405.11
   816.8 2413.87   827.9 2415.75   866.3 2425.46     900 2431.48   915.8 2433.15
#Mann= 5 ,-1 , 0
       0      .1       0  142.63     .06       0  246.93    .045       0
   298.7      .1       0  781.03      .1       0
Bank Sta=246.93,298.7
XS Rating Curve= 0 ,0
Exp/Cntr=0.3,0.1

Type RM Length L Ch R = 1 ,44172   ,372.3,374.8,377.3
XS GIS Cut Line= 3
 2233621.0238103385861.9389685542233321.02375413386253.605508059
2233078.31557813386521.313962147
#Sta/Elev= 30
       0 2442.54    27.9 2426.75    37.4 2420.09    49.5 2414.78    56.7 2410.04
    71.1 2402.35    76.5 2400.44   111.8 2392.77   132.5 2382.83   250.9 2380.65
   276.1 2381.55   297.7 2379.35   308.5 2379.96   318.8 2378.34   337.5 2377.72
   346.9 2378.28   353.9 2379.96   376.3 2379.44   384.6 2380.88   400.7 2380.27
   417.1 2381.52   475.5 2380.97   494.3 2382.23   567.2 2381.97   607.1 2382.78
     643 2385.33   677.7 2394.51   750.9 2418.14   819.3 2443.01   854.7  2453.9
#Mann= 7 ,-1 , 0
       0      .1       0    57.6     .12       0   66.96     .06       0
  260.46     .12       0   308.5    .045       0   353.9     .12       0
  520.69      .1       0
#XS Ineff= 2 , 0
          164.12  2389.9  498.02         2388.02
Permanent Ineff=
       F       F
Bank Sta=308.5,353.9
XS Rating Curve= 0 ,0
Exp/Cntr=0.3,0.1

Type RM Length L Ch R = 1 ,43797   ,413.7,416.4,418
XS GIS Cut Line= 3
2233501.62542705385509.6112611442233158.78621772 385858.59612748
2232735.60727406386310.897060141
#Sta/Elev= 30
       0 2512.55    30.7 2499.41    97.3 2476.12   125.4 2463.35   144.4 2453.85
   209.6 2413.32   230.2 2402.52   261.1 2393.13     323 2387.54   404.2 2383.92
   420.5 2382.34   429.8 2382.22     439 2383.47   485.4 2382.51   494.1 2380.78
   499.3  2377.5     505 2376.09   520.2 2375.68     548 2377.02   565.9 2376.85
   589.9 2378.63   637.8 2378.21   655.8 2376.74   745.4 2376.94   922.8 2381.71
   929.9 2384.86  1001.8 2428.56  1033.2 2448.91  1073.6 2477.07  1108.6  2497.9
#Mann= 9 ,-1 , 0
       0      .1       0   146.3     .12       0     323     .06       0
  442.75     .12       0   499.3    .045       0     548     .12       0
  593.83      .1       0  749.35      .1       0 1063.15      .1       0
Bank Sta=499.3,548
XS Rating Curve= 0 ,0
Exp/Cntr=0.3,0.1

Type RM Length L Ch R = 1 ,43381   ,392.2,401.8,404.6
XS GIS Cut Line= 3
2233282.48216455385262.9805208152232828.31542197385609.855483234
2232397.06562831385989.022047728
#Sta/Elev= 30
       0 2457.41    49.5  2430.9    84.4 2416.13   120.8 2405.33   132.5 2404.85
   165.3 2397.96   284.4 2383.79   455.5 2378.45   511.5 2373.23   518.7 2371.18
   535.1 2372.87   557.3 2375.15   595.8 2373.97   602.7 2372.22   616.7 2374.71
   670.2 2373.28   696.2 2374.42   760.8 2370.98     805 2372.19   816.6 2370.97
   900.3 2372.97   914.3 2382.72   960.7 2424.33   997.9 2454.86  1041.3 2489.05
    1077 2514.68  1098.1 2527.76  1107.2 2531.29  1124.3 2535.21  1145.7 2537.26
#Mann= 6 ,-1 , 0
       0     .12       0   388.9     .06       0   511.5    .045       0
   535.1     .06       0  583.07      .1       0 1043.37      .1       0
Bank Sta=511.5,535.1
XS Rating Curve= 0 ,0
Exp/Cntr=0.3,0.1

Type RM Length L Ch R = 1 ,42979   ,420.2,427.8,422.3
XS GIS Cut Line= 4
2233269.98218955385190.063999981 2232664.7737543385378.605617642
2232493.94043456 385480.688746812232104.35722423385774.438815475
#Sta/Elev= 30
       0  2438.4    31.5 2435.94    62.5 2429.05   100.3 2415.47   134.6 2400.01
   230.8 2391.19   368.3 2384.34   388.9 2384.32   553.9 2378.11   651.9 2376.56
   665.2 2373.81   682.5 2375.24   720.7 2373.69     737 2370.25   787.2 2370.09
   816.2 2367.02   827.9 2370.12   861.6 2368.47   879.5 2369.39   905.3 2366.54
   921.8 2370.14   958.8 2369.21   999.9 2371.99  1008.1 2373.69  1024.8    2383
  1049.2 2401.94  1069.7 2415.92  1095.9 2429.21  1131.4 2445.01  1320.8 2511.46
#Mann= 6 ,-1 , 0
       0     .12       0   388.9      .1       0   553.9     .06       0
   720.7      .1       0   787.2    .045       0   827.9      .1       0
Bank Sta=787.2,827.9
XS Rating Curve= 0 ,0
Exp/Cntr=0.5,0.3

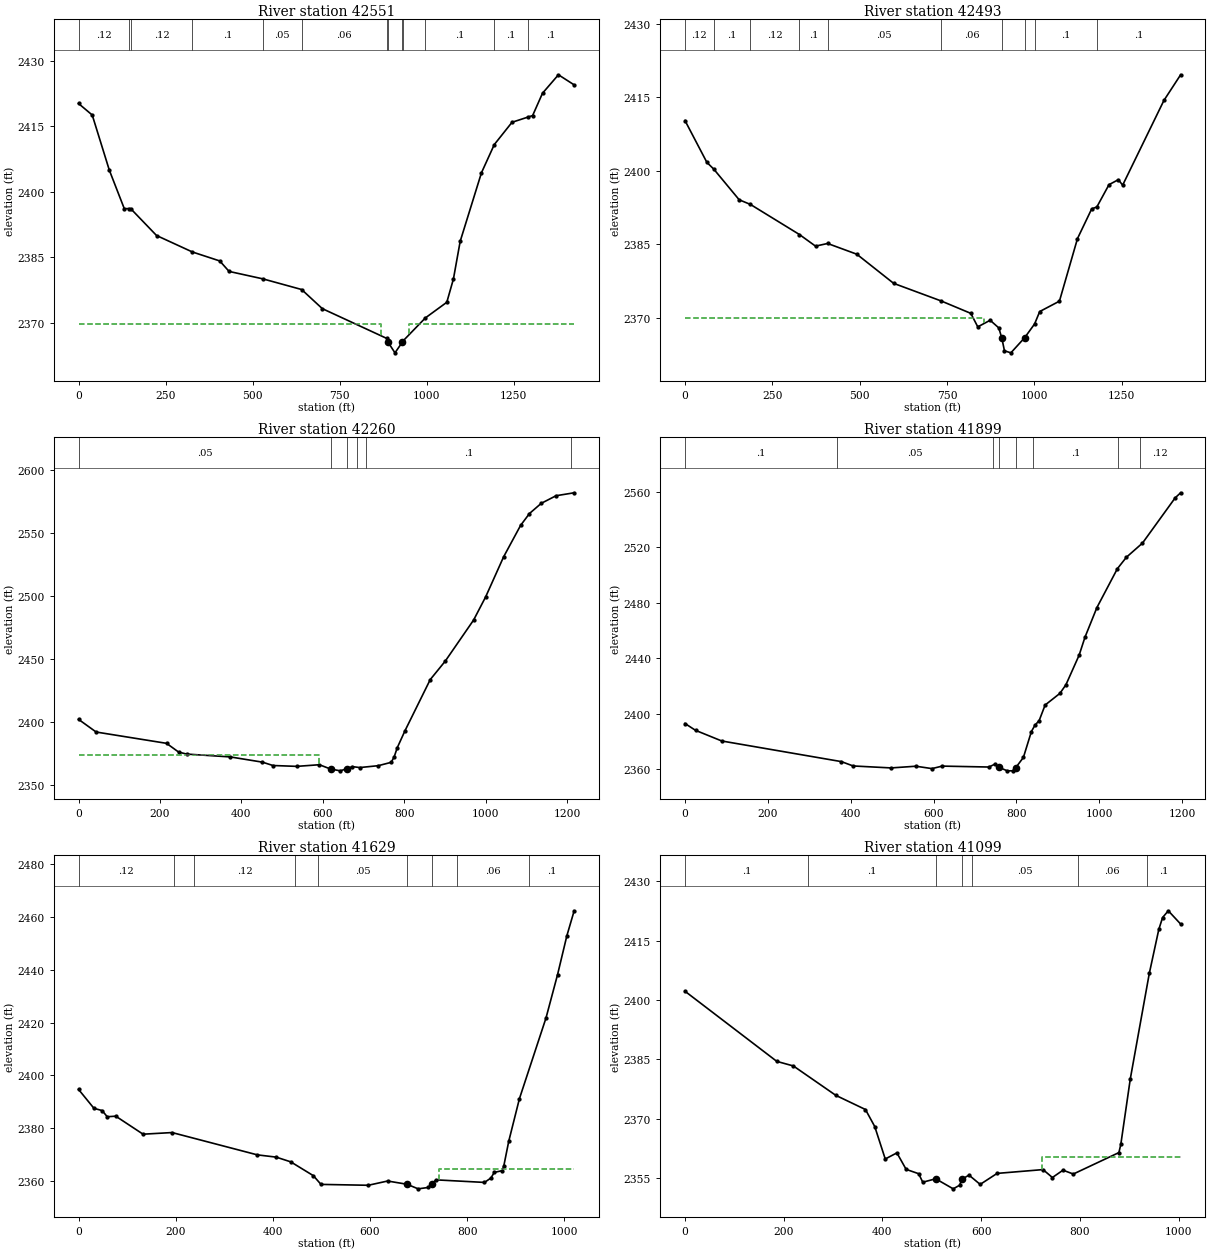
Type RM Length L Ch R = 1 ,42551   ,58.7,58.4,58.1
XS GIS Cut Line= 5
2233252.27389164385158.813734397 2232379.3570023385269.230508313
2232312.69046897385282.7721478942232274.14887939385303.605439559
2231912.69061281385540.063956141
#Sta/Elev= 30
       0 2420.22    39.4 2417.58    88.5 2404.96   131.5 2396.15   144.8 2396.17
   151.4 2396.03   224.1 2390.01   327.1 2386.24   405.6 2384.19   432.5 2381.79
   528.9  2380.1   640.8 2377.65   700.3 2373.27   885.6 2366.45     889  2365.6
   908.9 2363.16   930.3 2365.63   931.2 2365.81   996.2 2371.15  1057.8 2374.73
  1076.8 2380.06  1096.2 2388.67  1157.3 2404.36  1194.2 2410.82  1245.1 2415.92
    1291 2417.11  1304.3 2417.46  1332.7 2422.57  1378.4 2426.79  1423.6 2424.48
#Mann= 13 ,-1 , 0
       0     .12       0   144.8      .1       0   151.4     .12       0
   327.1      .1       0   528.9     .05       0   640.8     .06       0
   885.6      .1       0     889    .045       0   930.3    .045       0
   931.2      .1       0   996.2      .1       0  1194.2      .1       0
    1291      .1       0
#XS Ineff= 2 , 0
             869  2369.8   950.3          2369.8
Permanent Ineff=
       F       F
Bank Sta=889,930.3
XS Rating Curve= 0 ,0
Exp/Cntr=0.5,0.3

Type RM Length L Ch R = 1 ,42493   ,234.8,232.7,221.3
XS GIS Cut Line= 6
2233259.56554373385118.1888156382232460.60716788385202.563974977
2232390.81564081385204.6473041472232297.06550021385233.813912481
2232219.98199297385258.8138624732231894.98231488 385426.52218847
#Sta/Elev= 30
       0 2410.26    62.7  2401.7      82 2400.36   155.1 2394.06   187.3 2393.11
   327.5 2386.96   373.5 2384.59   408.1 2385.13   491.6 2382.94   597.1 2376.98
   732.4  2373.4   817.8 2370.85   837.8 2368.09   873.2 2369.44     898 2367.87
  906.742365.736   914.1  2363.2   932.5 2362.78     972 2365.88  1000.4 2368.69
    1015 2371.22  1071.4 2373.34  1123.1 2386.14  1163.7  2392.2  1178.5  2392.6
  1213.2 2397.15    1240 2398.17  1252.3 2397.05  1370.4 2414.37  1418.2 2419.61
#Mann= 10 ,-1 , 0
       0     .12       0      82      .1       0   187.3     .12       0
   327.5      .1       0   408.1     .05       0   732.4     .06       0
  906.74    .045       0     972      .1       0  1000.4      .1       0
  1178.5      .1       0
#XS Ineff= 2 , 0
          856.74  2369.8
Permanent Ineff=
       F       F
Bank Sta=906.74,972
XS Rating Curve= 0 ,0
Exp/Cntr=0.5,0.3

Type RM Length L Ch R = 1 ,42260   ,359.6,360.4,362.4
XS GIS Cut Line= 2
 2232769.9822053384746.3139032272231684.56541289385298.397116646
#Sta/Elev= 30
       0 2402.01    43.3 2391.92   216.3 2382.93   245.8 2376.02   265.6 2374.39
     373 2372.13   451.9 2367.97   477.7 2365.31   536.3 2364.62   591.8 2365.93
   619.3 2362.52   643.3 2361.07   659.3 2362.84   673.1  2364.4   691.2 2363.68
   736.5 2365.17   768.3 2367.84   775.6 2372.21   783.2 2379.48   802.4 2393.12
   864.2 2433.61     901 2448.25   970.8 2480.97  1000.4 2499.39  1044.5 2531.19
  1086.2 2556.17    1108 2565.59  1136.9 2573.68  1173.3 2579.73  1217.8 2582.08
#Mann= 6 ,-1 , 0
       0     .05       0   619.3    .045       0   659.3     .05       0
  683.53     .06       0  705.28      .1       0 1211.14      .1       0
#XS Ineff= 2 , 0
          591.85 2373.87
Permanent Ineff=
       F       F
Bank Sta=619.3,659.3
XS Rating Curve= 0 ,0
Exp/Cntr=0.3,0.1

Type RM Length L Ch R = 1 ,41899   ,265.1,270.8,272.6
XS GIS Cut Line= 3
2232679.35705847384494.2304178922231999.14877322384760.897207394
 2231571.0239733384944.230502144
#Sta/Elev= 30
       0 2393.05    25.5 2388.12    88.8 2380.44   377.6 2365.56   405.8 2362.43
   497.4 2361.01   557.3 2362.24   596.1 2360.52   620.7 2362.32   733.6 2361.66
   747.8 2363.72   758.5  2361.4   777.8 2358.91   790.7 2358.93   797.8    2361
   816.8 2368.57   836.1 2387.25   844.3 2391.64   854.9  2395.2   869.2 2406.36
   904.9 2414.77   919.5 2421.03   951.3 2442.33   965.5 2455.35   994.2 2476.66
  1043.7 2504.74  1065.5 2512.99  1104.2 2523.16  1183.2 2555.83  1196.3 2559.46
#Mann= 8 ,-1 , 0
       0      .1       0  366.93     .05       0  743.16     .06       0
   758.5    .045       0   797.8     .06       0  841.03      .1       0
 1045.74      .1       0 1098.34     .12       0
Bank Sta=758.5,797.8
XS Rating Curve= 0 ,0
Exp/Cntr=0.3,0.1

Type RM Length L Ch R = 1 ,41629   ,529.6,529.4,515.5
XS GIS Cut Line= 3
2232612.69052514384324.4387627242232231.44063146384470.272132471
 2231627.2738608384569.230595976
#Sta/Elev= 30
       0 2394.73    31.8 2387.55    48.6 2386.71    59.1 2384.37    76.7 2384.58
   132.9 2377.76   192.6 2378.38   368.2 2369.93   406.9 2369.08   436.9 2367.29
   483.4 2362.06   499.2 2358.75   596.6 2358.42   636.3 2360.03   676.2 2358.81
   699.2 2357.07   719.5 2357.58  726.912358.922   736.1 2360.47   835.8  2359.5
   849.1 2361.18   855.8 2363.29   872.4 2363.96   875.7 2365.88   885.7 2375.08
   907.7  2391.2   962.4 2421.75   986.2 2438.17  1005.4 2452.92  1020.4 2462.35
#Mann= 9 ,-1 , 0
       0     .12       0  196.98      .1       0  238.38     .12       0
  446.11      .1       0   493.2     .05       0   676.2    .045       0
  726.91     .05       0   778.2     .06       0  926.89      .1       0
#XS Ineff= 2 , 0
                           741.6         2364.62
Permanent Ineff=
       F       F
Bank Sta=676.2,726.91
XS Rating Curve= 0 ,0
Exp/Cntr=0.3,0.1

Type RM Length L Ch R = 1 ,41099   ,414.1,418.9,417.9
XS GIS Cut Line= 3
2232428.31556581383928.6055648922231911.64894822384212.980652317
2231558.52367023384429.647213727
#Sta/Elev= 30
       0 2402.23     186 2384.52   219.6 2383.36   305.7 2375.93   365.6 2372.36
   384.4 2368.07   405.7 2359.87   429.3 2361.41     448 2357.25   473.4 2356.15
   481.7    2354   507.9 2354.87   543.4 2352.33   556.6 2353.26   560.5 2354.73
   575.4 2355.79     598 2353.45   632.3 2356.23   725.3 2357.19   744.3 2355.19
   765.8 2357.04   786.7 2356.07     879 2361.48   882.9 2363.55   902.1 2380.08
   940.6 2406.72   959.9 2417.86   967.6 2420.85   979.1 2422.55  1004.1  2419.2
#Mann= 7 ,-1 , 0
       0      .1       0  248.86      .1       0   507.9    .045       0
   560.5      .1       0   581.5     .05       0  795.36     .06       0
  935.86      .1       0
#XS Ineff= 2 , 0
                          723.26         2360.25
Permanent Ineff=
       F       F
Bank Sta=507.9,560.5
XS Rating Curve= 0 ,0
Exp/Cntr=0.3,0.1

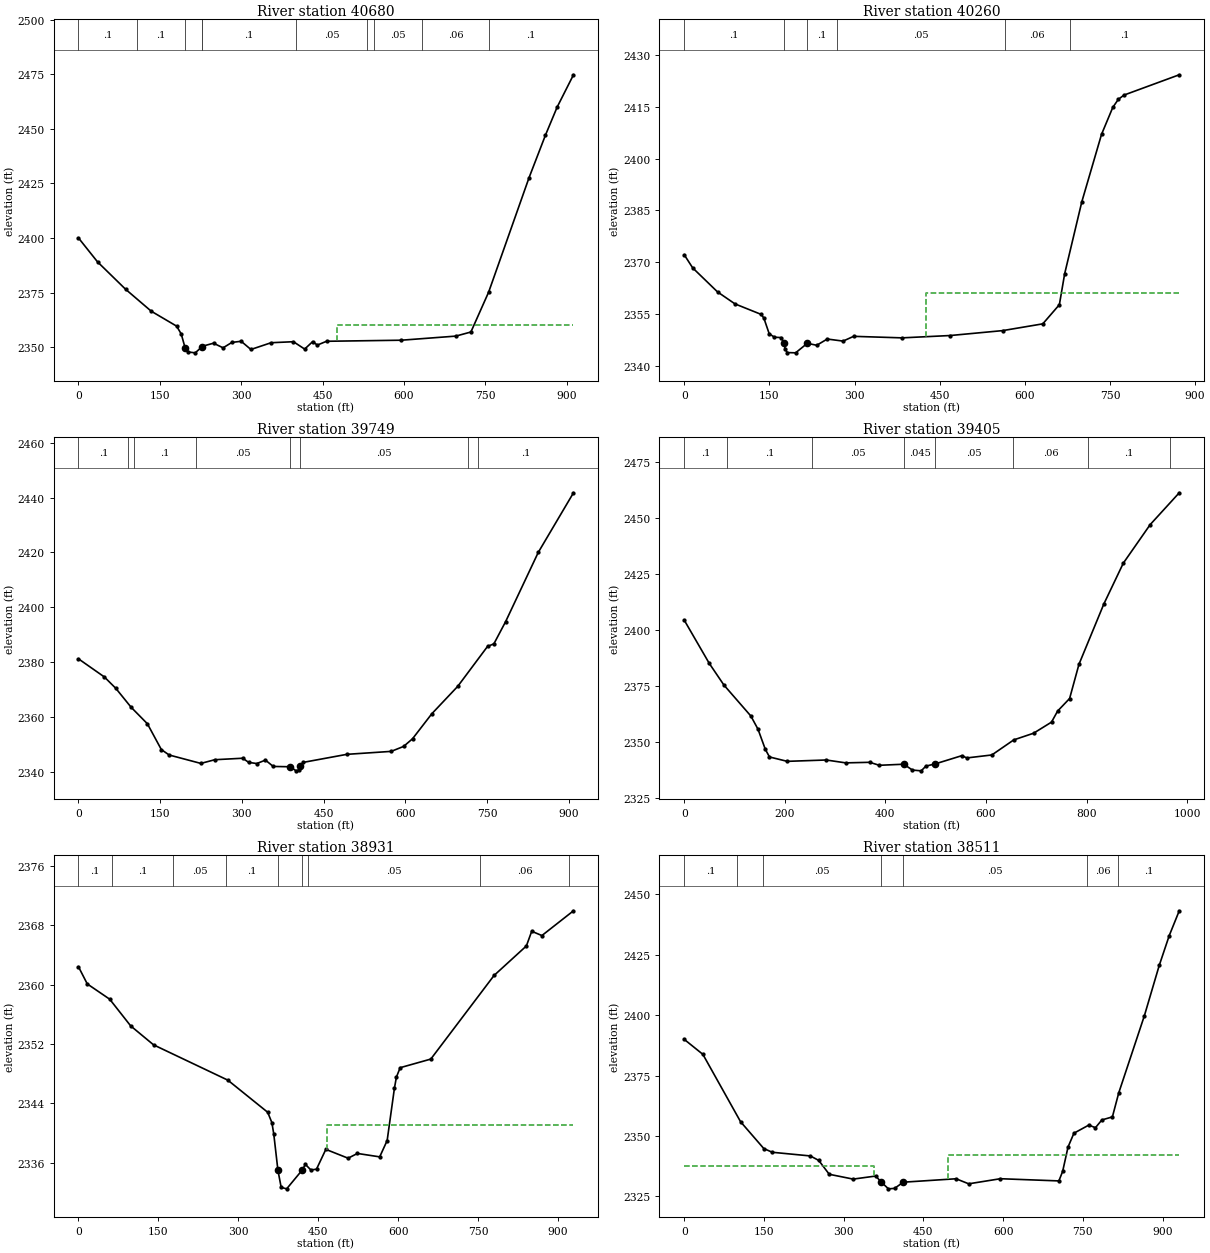
Type RM Length L Ch R = 1 ,40680   ,422.8,420.9,417.8
XS GIS Cut Line= 2
2232060.60731173383651.5221295652231356.44041297384231.730614811
#Sta/Elev= 30
       0 2400.03    35.1 2389.07    86.7 2376.54   134.1 2366.45   180.9  2359.6
   189.4    2356   196.6 2349.58   202.2 2347.75   215.2 2347.36   226.9 2349.97
   227.7 2350.33   248.9 2351.78   266.5 2349.66   282.8 2352.14   299.9 2352.66
   317.8  2348.9   355.1    2352   396.2 2352.46   416.9 2349.08   431.7 2352.52
   440.2 2350.91   457.2 2352.66   595.1 2353.15   695.5 2355.03   723.3 2356.91
     756 2375.19   830.5 2427.67   860.8 2447.21   882.3 2460.03   912.4 2474.84
#Mann= 10 ,-1 , 0
       0      .1       0  107.87      .1       0   196.6    .045       0
   226.9    .045       0   227.7      .1       0  400.01     .05       0
  532.41      .1       0  544.15     .05       0   633.7     .06       0
   756.6      .1       0
#XS Ineff= 2 , 0
                          475.95         2360.23
Permanent Ineff=
       F       F
Bank Sta=196.6,226.9
XS Rating Curve= 0 ,0
Exp/Cntr=0.3,0.1

Type RM Length L Ch R = 1 ,40260   ,513.9,510.9,503.1
XS GIS Cut Line= 2
2231717.89867955383357.7720609012231137.69052239 384008.81373781
#Sta/Elev= 30
       0 2372.16    14.9 2368.36    58.6 2361.41    89.4 2357.93   135.8 2354.87
   140.4 2353.76   149.7 2349.27     159 2348.27     171 2348.17   175.3  2346.7
     178 2344.77   181.6 2343.83   196.2 2343.75   216.8 2346.51   233.4 2345.94
     252 2347.75   279.8 2347.15   298.4 2348.53   383.8 2348.09   468.9 2348.77
     561 2350.19   631.7 2352.15   660.9  2357.7   670.2 2366.65   700.4 2387.49
   735.2 2407.06     755 2414.86   764.8  2417.2   774.8 2418.43   872.1 2424.31
#Mann= 6 ,-1 , 0
       0      .1       0   175.3    .045       0   216.8      .1       0
  268.32     .05       0  564.26     .06       0   679.1      .1       0
#XS Ineff= 2 , 0
                          426.15         2361.11
Permanent Ineff=
       F       F
Bank Sta=175.3,216.8
XS Rating Curve= 0 ,0
Exp/Cntr=0.3,0.1

Type RM Length L Ch R = 1 ,39749   ,339.1,343.6,350.9
XS GIS Cut Line= 3
2231372.06538172383031.730390146 2231062.6903443383405.688959807
2230786.64890164383726.522307649
#Sta/Elev= 30
       0 2381.15    47.5 2374.54    68.5 2370.39    96.5 2363.51   126.5 2357.46
   152.1 2348.05   166.4 2346.07   224.6    2343   250.3 2344.35   301.5 2344.89
   312.4 2343.38   327.2 2342.95   343.2  2344.2   357.5 2341.89  388.762341.779
   399.4 2340.29   404.1 2340.57   407.5 2341.94   411.8 2343.35   492.6 2346.31
     574 2347.39   596.7 2349.19   613.1 2351.98   648.6 2361.12   696.2 2371.13
   750.8 2385.67   762.5 2386.63   784.1 2394.75   843.9 2419.97   908.6 2441.73
#Mann= 8 ,-1 , 0
       0      .1       0   91.37      .1       0   102.8      .1       0
  215.74     .05       0  388.76    .045       0   407.5     .05       0
   714.9     .06       0  732.89      .1       0
Bank Sta=388.76,407.5
XS Rating Curve= 0 ,0
Exp/Cntr=0.3,0.1

Type RM Length L Ch R = 1 ,39405   ,475.7,473.9,459.5
XS GIS Cut Line= 2
2231157.48214947382834.8554558162230490.81550381383558.813981637
#Sta/Elev= 30
       0  2404.4    49.8 2385.13    78.9  2375.5   132.5 2361.69   146.7 2355.81
   161.2 2346.86   169.5 2343.46   204.8 2341.51   282.3 2342.11     321 2340.83
   368.9 2341.08   387.8 2339.75   436.5 2340.23   453.7 2337.62   471.2 2337.28
   480.4 2339.38   499.2 2340.39   551.8 2344.03   561.9 2343.03   611.6 2344.35
   655.2 2351.07   694.5 2354.03   730.2 2358.98   742.4 2363.92   766.2  2369.5
   784.8 2384.74   834.4 2411.67     873 2429.81   926.4 2446.97   984.2 2461.15
#Mann= 8 ,-1 , 0
       0      .1       0   84.49      .1       0   254.4     .05       0
   436.5    .045       0   499.2     .05       0  653.14     .06       0
  803.11      .1       0  965.21      .1       0
Bank Sta=436.5,499.2
XS Rating Curve= 0 ,0
Exp/Cntr=0.3,0.1

Type RM Length L Ch R = 1 ,38931   ,409.5,420.6,435.9
XS GIS Cut Line= 4
2230717.89871106382458.8138850632230577.27366422382777.563903734
2230480.39885797383045.272357807 2230341.8571403383306.730496317
#Sta/Elev= 30
       0  2362.4    16.5 2360.09    58.6 2358.03      98 2354.43   140.9 2351.88
   280.3 2347.12   355.1 2342.79     363 2341.39   366.5 2339.86   374.3 2334.97
   380.4 2332.67   390.7 2332.47   420.1 2335.02   425.8 2335.77   436.2 2335.01
   446.7 2335.12   464.2 2337.79     506  2336.6   523.5 2337.24   565.3 2336.78
   579.3 2338.98     593 2346.06   596.7 2347.54   603.7  2348.8   661.2 2349.96
   779.9 2361.23   840.6 2365.21   850.6 2367.19   869.7 2366.61     929 2369.95
#Mann= 9 ,-1 , 0
       0      .1       0   62.11      .1       0  177.93     .05       0
  275.92      .1       0   374.3    .045       0   420.1      .1       0
  429.91     .05       0  753.96     .06       0  921.28      .1       0
#XS Ineff= 2 , 0
                          465.76         2341.11
Permanent Ineff=
       F       F
Bank Sta=374.3,420.1
XS Rating Curve= 0 ,0
Exp/Cntr=0.3,0.1

Type RM Length L Ch R = 1 ,38511   ,479.6,492.3,505.3
XS GIS Cut Line= 2
2230584.56564438382351.5221048892229815.81554148 382877.56403181
#Sta/Elev= 30
       0 2389.98    35.1 2383.78     106 2355.89   149.7 2344.79   165.6 2343.25
   237.2 2341.73   253.1 2339.88   272.9 2334.13   317.9 2332.14   360.4 2333.41
   370.32330.989   384.3 2328.11   395.8  2328.3   412.1 2330.86   511.5 2332.28
   535.3 2330.19     595  2332.3     705 2331.39   712.1 2335.35   722.2 2345.41
   733.3 2351.14   761.3  2354.5   773.8 2353.42   785.8 2356.62   805.7  2357.9
   817.6 2367.81   865.9 2399.78   893.8 2420.58   912.7 2432.97   931.5 2443.22
#Mann= 7 ,-1 , 0
       0      .1       0   99.34      .1       0   148.8     .05       0
   370.3    .045       0   412.1     .05       0  757.81     .06       0
  815.96      .1       0
#XS Ineff= 2 , 0
           357.1 2337.41  495.76         2342.16
Permanent Ineff=
       F       F
Bank Sta=370.3,412.1
XS Rating Curve= 0 ,0
Exp/Cntr=0.3,0.1

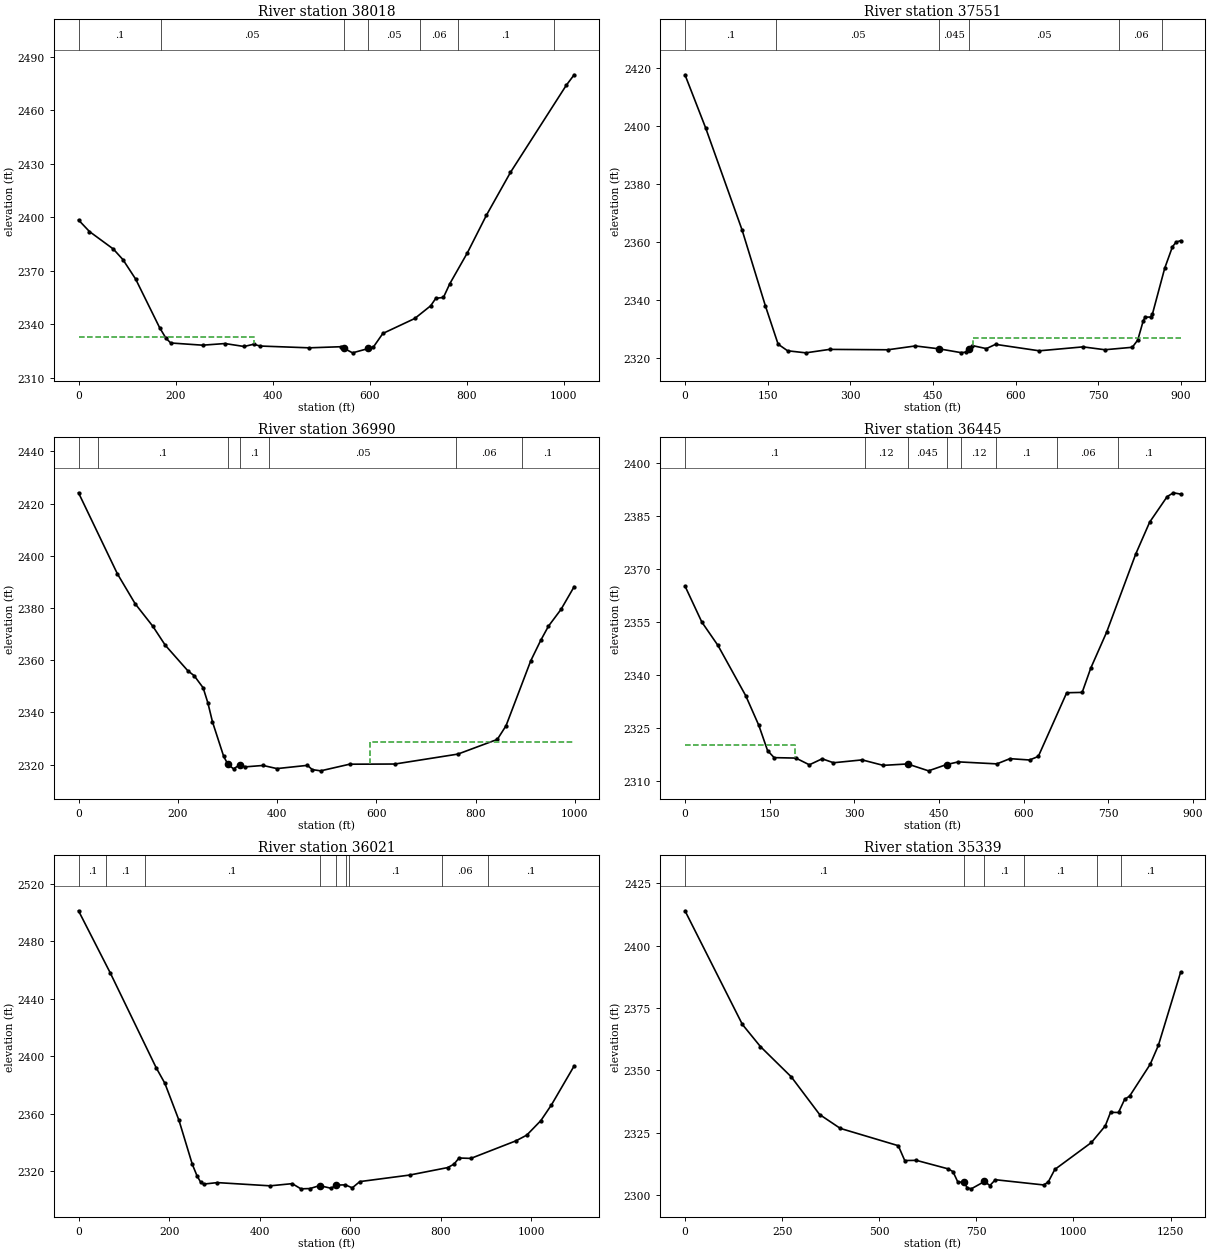
Type RM Length L Ch R = 1 ,38018   ,462.8,467.4,472.3
XS GIS Cut Line= 2
2230572.06534131 382190.063766392229552.27374572382249.438975722
#Sta/Elev= 30
       0 2398.45    22.5 2391.98    71.7 2382.17    91.5 2376.24   117.8 2365.28
   167.1 2338.09   180.4 2332.07   190.1 2329.48   255.8 2328.24   301.8 2329.16
   341.3 2327.51     361 2328.77   374.1 2327.77   475.5 2326.76   541.8 2327.39
   546.9 2326.49   564.8 2323.95   597.6 2326.39   607.5 2327.13   627.2 2334.81
     693 2343.21   725.8 2350.34   736.3 2354.51   752.1 2355.02   765.2  2362.7
   801.4 2380.02   840.8 2401.18   890.1 2425.08  1005.1 2473.92  1021.5 2479.86
#Mann= 7 ,-1 , 0
       0      .1       0  168.97     .05       0   546.9    .045       0
   597.6     .05       0  703.89     .06       0  782.36      .1       0
  979.66      .1       0
#XS Ineff= 2 , 0
          361.75 2332.67
Permanent Ineff=
       F       F
Bank Sta=546.9,597.6
XS Rating Curve= 0 ,0
Exp/Cntr=0.3,0.1

Type RM Length L Ch R = 1 ,37551   ,570.5,561.1,552.6
XS GIS Cut Line= 2
2230543.94039756381826.5221706482229652.27387381381708.813744649
#Sta/Elev= 30
       0 2417.82    37.3 2399.57   103.5 2364.29   146.1  2337.9     169 2324.78
   186.2  2322.5   219.3 2321.79   262.3 2322.98   368.2 2322.85   417.9 2324.17
   460.9 2323.18   500.6 2321.87   510.5 2322.02  516.142323.184     521 2324.31
   546.9 2323.25   563.5 2324.72   642.9 2322.49   722.3 2323.85     762 2322.86
   811.7 2323.71   821.6 2326.21   831.5 2332.83   834.9 2334.11   844.8 2334.15
   848.1  2335.1   870.5 2351.01   884.5 2358.41   891.1 2360.02   899.4 2360.54
#Mann= 6 ,-1 , 0
       0      .1       0  165.66     .05       0   460.9    .045       0
  516.14     .05       0  787.08     .06       0  865.83      .1       0
#XS Ineff= 2 , 0
                          523.49         2326.78
Permanent Ineff=
       F       F
Bank Sta=460.9,516.14
XS Rating Curve= 0 ,0
Exp/Cntr=0.3,0.1

Type RM Length L Ch R = 1 ,36990   ,531.6,545.2,564.1
XS GIS Cut Line= 2
2230338.73214656381073.3973645572229512.69049156 381634.85555923
#Sta/Elev= 30
       0 2424.11    78.3  2393.1   114.2 2381.61   149.7 2373.02   174.8 2365.75
   220.4 2355.94     233 2354.09   251.1 2349.46   260.6 2343.73     270 2336.38
   292.5  2323.2   301.2  2320.1   312.5 2318.41  325.182320.014   335.8 2319.17
   371.8 2319.71   399.9 2318.51   461.3 2319.75     471 2318.12     488 2317.65
   546.3 2320.19   637.6 2320.26   764.5 2324.06   843.9 2329.68   861.5 2334.91
   911.3 2359.78   931.3 2367.56     947 2373.04   972.4 2379.49   998.8 2388.17
#Mann= 7 ,-1 , 0
       0      .1       0   38.86      .1       0   301.2    .045       0
  325.18      .1       0  383.79     .05       0  760.72     .06       0
  893.08      .1       0
#XS Ineff= 2 , 0
                             588         2328.84
Permanent Ineff=
       F       F
Bank Sta=301.2,325.18
XS Rating Curve= 0 ,0
Exp/Cntr=0.3,0.1

Type RM Length L Ch R = 1 ,36445   ,424.6,423.3,417.4
XS GIS Cut Line= 2
2229958.52391747 380840.063841732229213.73209997381305.688894734
#Sta/Elev= 30
       0 2365.16    29.9 2354.94    58.5 2348.32   107.7 2334.09   130.9 2325.69
   146.4 2318.55     158 2316.57   196.6 2316.44   220.4 2314.54   243.1 2316.24
   263.2 2315.12     314 2315.93   351.3 2314.38   394.4 2314.78   431.6 2312.83
   463.7 2314.62   484.7 2315.37   552.7  2314.8   575.9 2316.28   610.7  2315.9
   626.2 2316.92   676.5 2334.94   703.9 2335.04   719.1  2341.9   747.2 2352.07
   798.9 2374.25   823.5 2383.24   854.5 2390.47   865.6 2391.56   878.4 2391.18
#Mann= 8 ,-1 , 0
       0      .1       0  319.26     .12       0   394.4    .045       0
   463.7      .1       0  489.26     .12       0  551.69      .1       0
  659.43     .06       0  767.18      .1       0
#XS Ineff= 2 , 0
          194.68  2320.1
Permanent Ineff=
       F       F
Bank Sta=394.4,463.7
XS Rating Curve= 0 ,0
Exp/Cntr=0.3,0.1

Type RM Length L Ch R = 1 ,36021   ,680.5,682.3,680.6
XS GIS Cut Line= 5
2229791.59183663380379.2911412272229378.64220323380707.590681478
2229363.57858506380720.7471512262229348.51201414380733.898699731
2228932.53810856 381057.72712031
#Sta/Elev= 30
       0 2501.08    70.4 2457.73   171.7 2391.91   190.7 2381.23     222 2355.38
   251.3 2324.95   261.8 2316.87   269.8 2312.48   276.5 2311.19   306.7 2312.21
   423.2 2309.97     472 2311.49   491.2 2307.88   511.2 2308.08   532.3 2310.12
   558.4 2308.23     568 2310.49   589.4 2310.64   604.6 2308.57   621.3 2312.91
   731.2 2317.45   815.4 2322.65   829.4 2325.06   840.4 2329.31   866.5 2329.02
   966.3 2341.26     990  2345.2  1021.1 2355.28  1044.5  2366.2  1094.7 2393.29
#Mann= 9 ,-1 , 0
       0      .1       0   61.17      .1       0  146.21      .1       0
   532.3    .045       0     568      .1       0  589.97     .12       0
  598.29      .1       0  803.35     .06       0  904.63      .1       0
Bank Sta=532.3,568
XS Rating Curve= 0 ,0
Exp/Cntr=0.3,0.1

Type RM Length L Ch R = 1 ,35339   ,530,543.4,550.5
XS GIS Cut Line= 4
2229737.69036964380034.8554783912229213.73209997380112.980650231
2229079.35704064380133.813941896 2228590.8153668380499.438866809
#Sta/Elev= 30
       0 2414.03   147.7 2368.41   194.1 2359.53   273.8 2347.32   346.7 2332.21
   399.8 2326.66   549.1 2319.71   565.7 2313.75   595.6 2313.83   677.5 2310.41
   689.8 2309.31   702.9 2304.95     717 2305.26   726.7 2302.81   736.9 2302.39
   770.9 2305.34   784.9 2303.72     799 2306.05   923.4 2303.95     935 2305.12
     952 2310.17  1046.3    2321  1081.9 2327.66  1095.5 2333.11    1116 2333.04
  1131.8 2338.33  1144.7 2339.64  1197.5 2352.38  1218.6 2359.99  1275.9 2389.37
#Mann= 6 ,-1 , 0
       0      .1       0     717    .045       0   770.9      .1       0
  873.54      .1       0 1060.46     .06       0 1122.98      .1       0
Bank Sta=717,770.9
XS Rating Curve= 0 ,0
Exp/Cntr=0.3,0.1