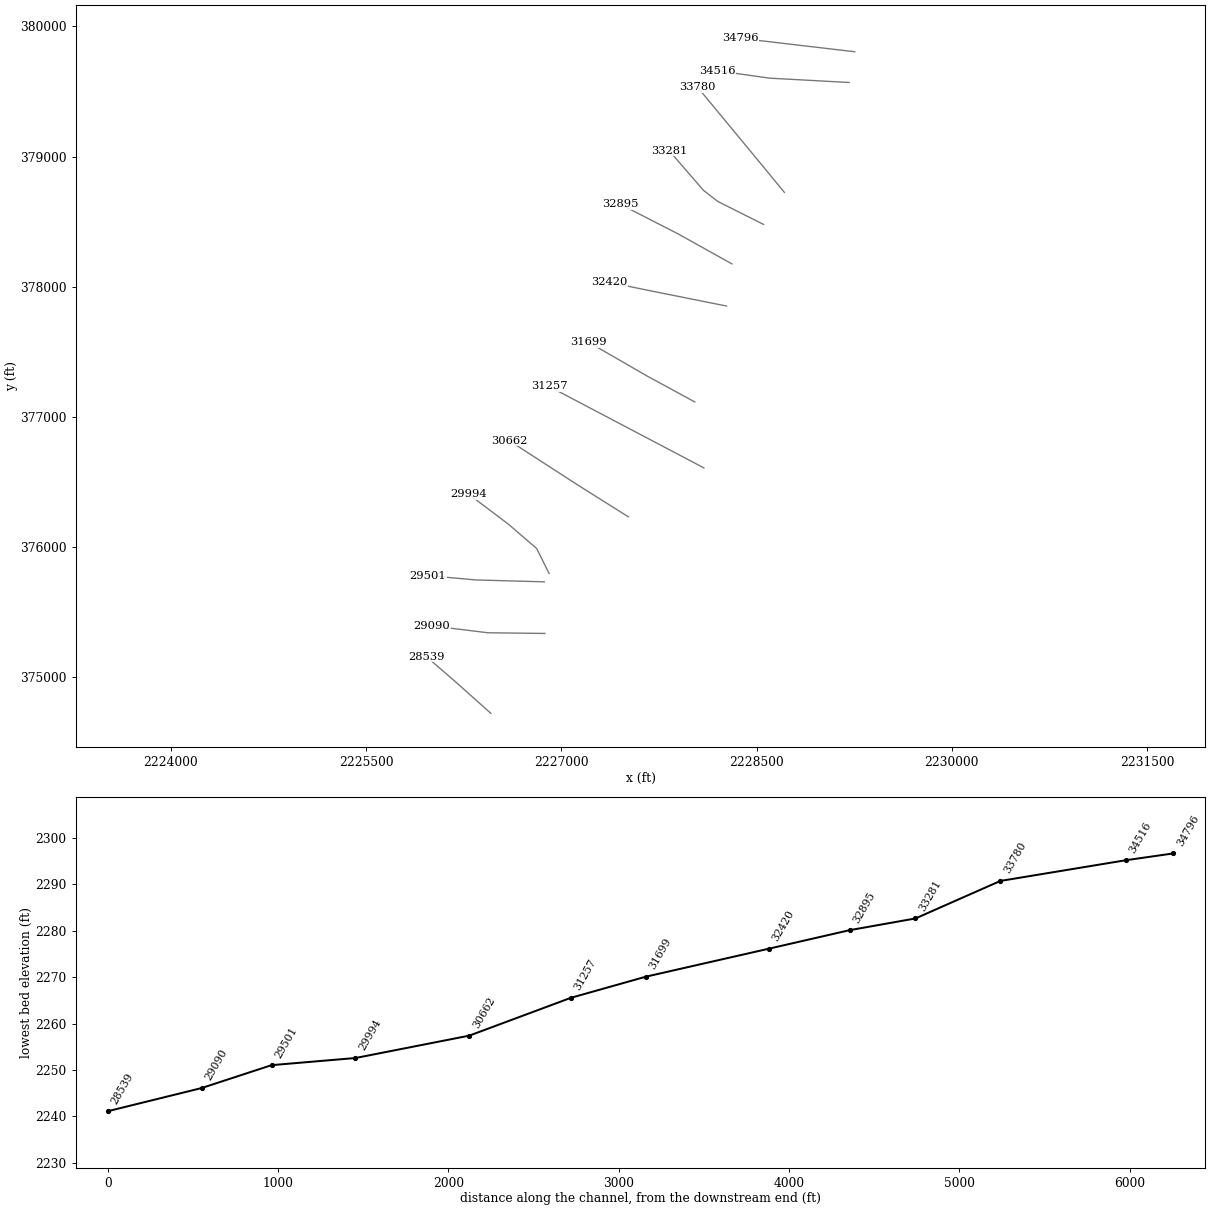
HEC-RAS study NFANTNYCK.prj: NFANTNYCK

--- NFANTNYCK.g01 (geometry) --- (continued)

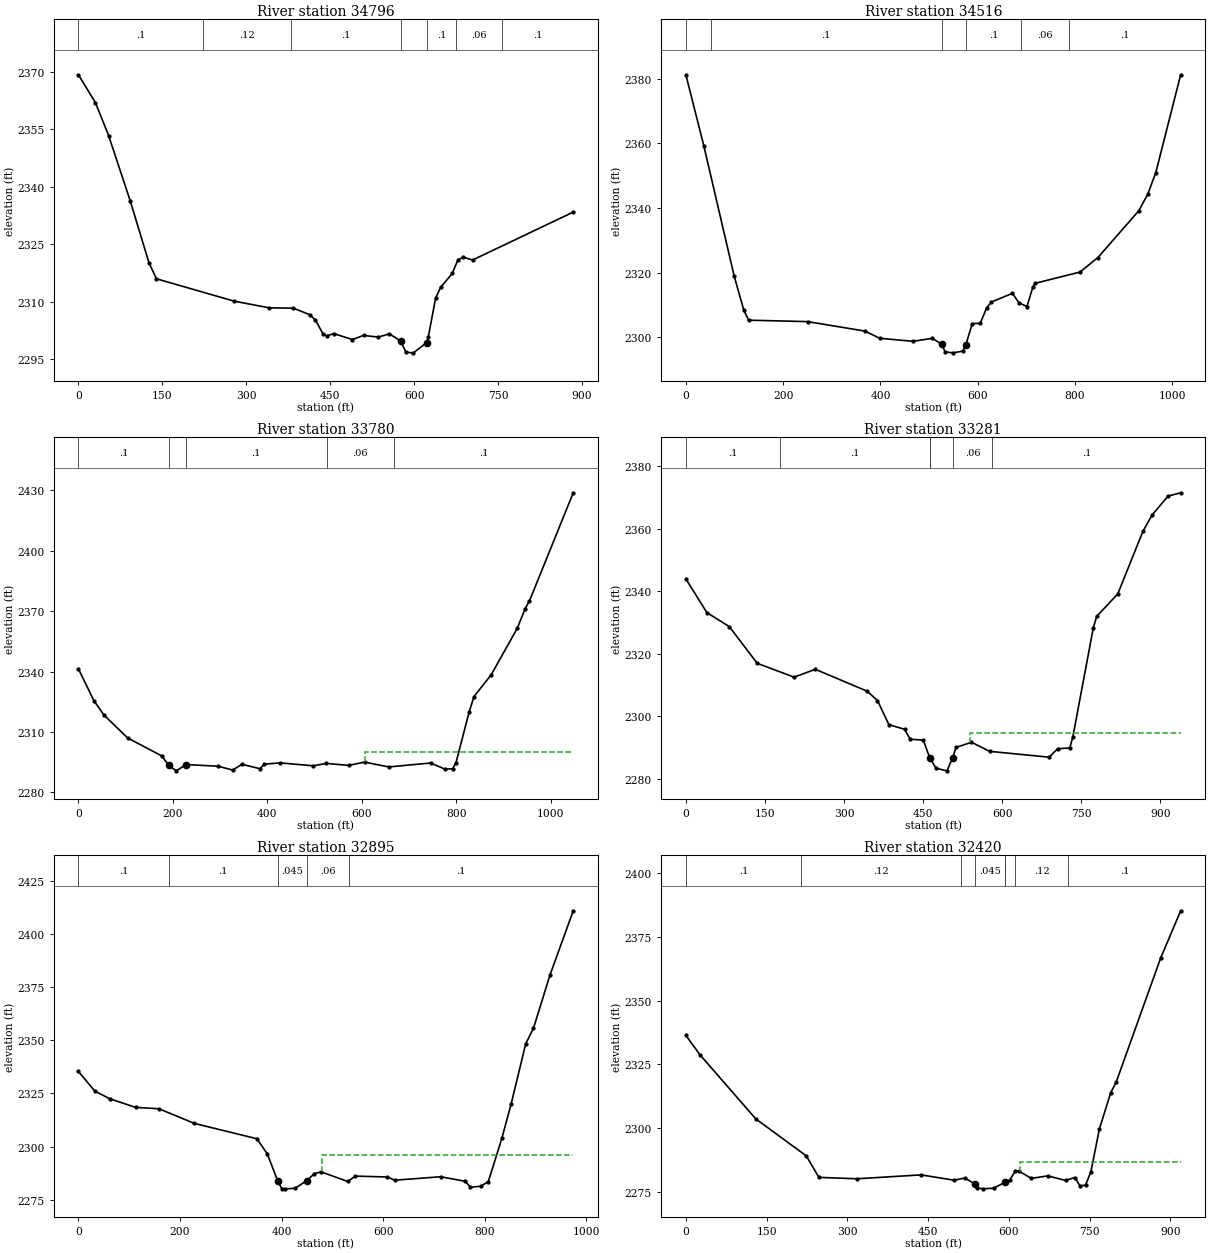
Type RM Length L Ch R = 1 ,34796   ,278.5,279.6,280.9
XS GIS Cut Line= 2
2229254.35701872 379805.688941972228376.23213455379908.813735724
#Sta/Elev= 30
       0 2369.28    30.4 2361.97    53.9  2353.4    92.3 2336.43   126.2  2320.1
   139.4    2316   278.2 2310.16   340.9 2308.41   383.9 2308.33   413.6 2306.61
   423.5 2305.18   436.7 2301.71   443.3 2301.12   456.6 2301.67   489.6 2300.13
   509.4 2301.21   535.8 2300.78   555.7 2301.62   575.5 2299.76   585.4  2296.8
   598.6 2296.66   622.1 2299.32     625 2300.68   638.2 2310.94   647.2 2313.75
     668  2317.4   678.2 2320.98   687.8 2321.64   704.3  2320.9   884.2 2333.42
#Mann= 7 ,-1 , 0
       0      .1       0  222.31     .12       0  380.14      .1       0
   575.5    .045       0   622.1      .1       0  675.08     .06       0
  757.63      .1       0
Bank Sta=575.5,622.1
XS Rating Curve= 0 ,0
Exp/Cntr=0.3,0.1

Type RM Length L Ch R = 1 ,34516   ,747.4,736.3,716.9
XS GIS Cut Line= 3
2229211.64877081379569.2304253882228601.23201264379602.564020142
 2228199.1488273379658.813907638
#Sta/Elev= 30
       0  2381.2    36.8 2359.28    99.2 2318.96   118.9 2308.47   128.8  2305.3
   250.3 2304.85   368.6 2301.91   398.2  2299.7   467.2 2298.75   506.6  2299.7
   526.3  2297.8   532.9  2295.5   549.2 2295.19   569.1 2295.71   575.6  2297.7
   588.8 2304.22   605.3 2304.34   618.4 2309.14   628.3 2310.94   671.4  2313.6
   684.7 2310.68   701.2  2309.5   713.2 2315.47   717.8  2316.7   810.5  2320.2
     847 2324.67   931.2 2339.16   949.7 2344.32   966.1 2350.95  1017.3 2381.24
#Mann= 6 ,-1 , 0
       0      .1       0   50.59      .1       0   526.3    .045       0
   575.6      .1       0  689.79     .06       0  788.27      .1       0
Bank Sta=526.3,575.6
XS Rating Curve= 0 ,0
Exp/Cntr=0.3,0.1

Type RM Length L Ch R = 1 ,33780   ,491.4,499,501.6
XS GIS Cut Line= 3
2228713.73211572 378724.438807892228546.02378972378928.605394304
2228047.06547005379532.772164971
#Sta/Elev= 30
       0 2341.26    32.6 2325.59    53.6 2318.51   104.3    2307   176.5 2298.13
  191.222293.383   207.5 2290.73   227.5 2293.84   295.5 2293.03   326.3 2291.14
   346.5 2293.96   384.3  2291.8   393.9 2294.03   426.5 2294.69   497.7 2293.22
   524.4 2294.43     572 2293.43   605.9 2295.06   657.1 2292.66   745.8 2294.63
   776.1 2291.56   792.4 2291.76   799.4  2294.7   827.4 2319.96   837.7  2327.6
   874.2 2338.45   929.5 2361.55   945.9 2371.19     955    2375  1047.8 2428.67
#Mann= 5 ,-1 , 0
       0      .1       0  191.22    .045       0   227.5      .1       0
  525.28     .06       0  668.42      .1       0
#XS Ineff= 2 , 0
                          607.81          2300.3
Permanent Ineff=
       F       F
Bank Sta=191.22,227.5
XS Rating Curve= 0 ,0
Exp/Cntr=0.3,0.1

Type RM Length L Ch R = 1 ,33281   ,382.8,385.9,387.8
XS GIS Cut Line= 4
2228554.35710639378477.5639735612228202.27382106378654.647280812
2228091.85704714378740.0637766422227827.27391489379046.313820317
#Sta/Elev= 30
       0 2343.92    39.8 2333.16    82.3 2328.69   135.3 2316.97   205.1 2312.56
   245.5 2315.06   343.7 2308.08   363.3  2305.1   385.1 2297.37   414.7 2295.92
   425.4 2292.72   450.2 2292.48   462.7 2286.67   474.5 2283.47   495.2 2282.64
   505.9 2286.85   512.5 2290.11   541.6 2291.77   576.2 2288.86     689    2287
   705.1 2289.72     728 2289.93   733.8  2293.4   772.6 2328.22     779 2331.93
   819.2 2339.17   866.7 2359.08   884.2 2364.34   914.5 2370.37   938.4 2371.43
#Mann= 6 ,-1 , 0
       0      .1       0  178.49      .1       0  462.28     .06       0
   462.7    .045       0   505.9     .06       0  581.44      .1       0
#XS Ineff= 2 , 0
                          539.33         2294.82
Permanent Ineff=
       F       F
Bank Sta=462.7,505.9
XS Rating Curve= 0 ,0
Exp/Cntr=0.3,0.1

Type RM Length L Ch R = 1 ,32895   ,468.4,475.2,485.5
XS GIS Cut Line= 3
 2228310.6072658378174.4389236422227896.02377738378405.688789234
2227451.23201606378633.813989148
#Sta/Elev= 30
       0 2335.29    32.1 2326.09    62.1 2322.41   112.8  2318.4   158.6 2317.75
   228.5 2310.86   351.5 2303.66   371.9 2296.57   392.8 2283.67   400.3 2280.26
   407.8 2280.12   426.6 2280.37  449.68 2283.98   464.9 2287.32   478.2 2288.07
   530.6 2283.57   545.5  2286.1   608.6 2285.69   622.9 2284.18   713.4  2285.8
   762.1 2283.66   771.9 2280.88   792.5 2281.35   807.3 2283.55     834 2303.86
   852.3 2320.06     881 2348.29   896.2 2355.56   928.9 2380.69   974.6 2410.81
#Mann= 5 ,-1 , 0
       0      .1       0  177.52      .1       0   392.8    .045       0
  449.68     .06       0  531.94      .1       0
#XS Ineff= 2 , 0
                          479.91         2296.18
Permanent Ineff=
       F       F
Bank Sta=392.8,449.68
XS Rating Curve= 0 ,0
Exp/Cntr=0.3,0.1

Type RM Length L Ch R = 1 ,32420   ,730,720.7,701.6
XS GIS Cut Line= 3
2228268.94035439377850.4805820582227660.60725348377972.355666399
2227367.89884938378032.772212222
#Sta/Elev= 30
       0 2336.32    26.3 2328.69     130 2303.54   223.7 2289.07   247.1 2280.62
   317.6 2280.07   437.1  2281.6   498.4  2279.5   518.4 2280.37   537.5 2277.94
   541.6 2276.48   551.9 2276.12   571.7 2276.38   593.2 2278.71   593.7 2278.75
   601.6 2279.49   611.8 2283.04   618.5  2283.1     642 2280.22   672.1 2281.21
   705.6 2279.42   722.4 2280.57   732.2 2277.32   742.5 2277.55   752.5 2282.88
   768.3 2299.63   789.4 2313.89   799.4 2317.97   882.1 2366.69   919.3 2385.25
#Mann= 8 ,-1 , 0
       0      .1       0  213.62     .12       0  511.81     .06       0
   537.5    .045       0   593.2    .045       0   593.7     .06       0
   611.2     .12       0  710.62      .1       0
#XS Ineff= 2 , 0
                          620.83         2286.73
Permanent Ineff=
       F       F
Bank Sta=537.5,593.2
XS Rating Curve= 0 ,0
Exp/Cntr=0.3,0.1

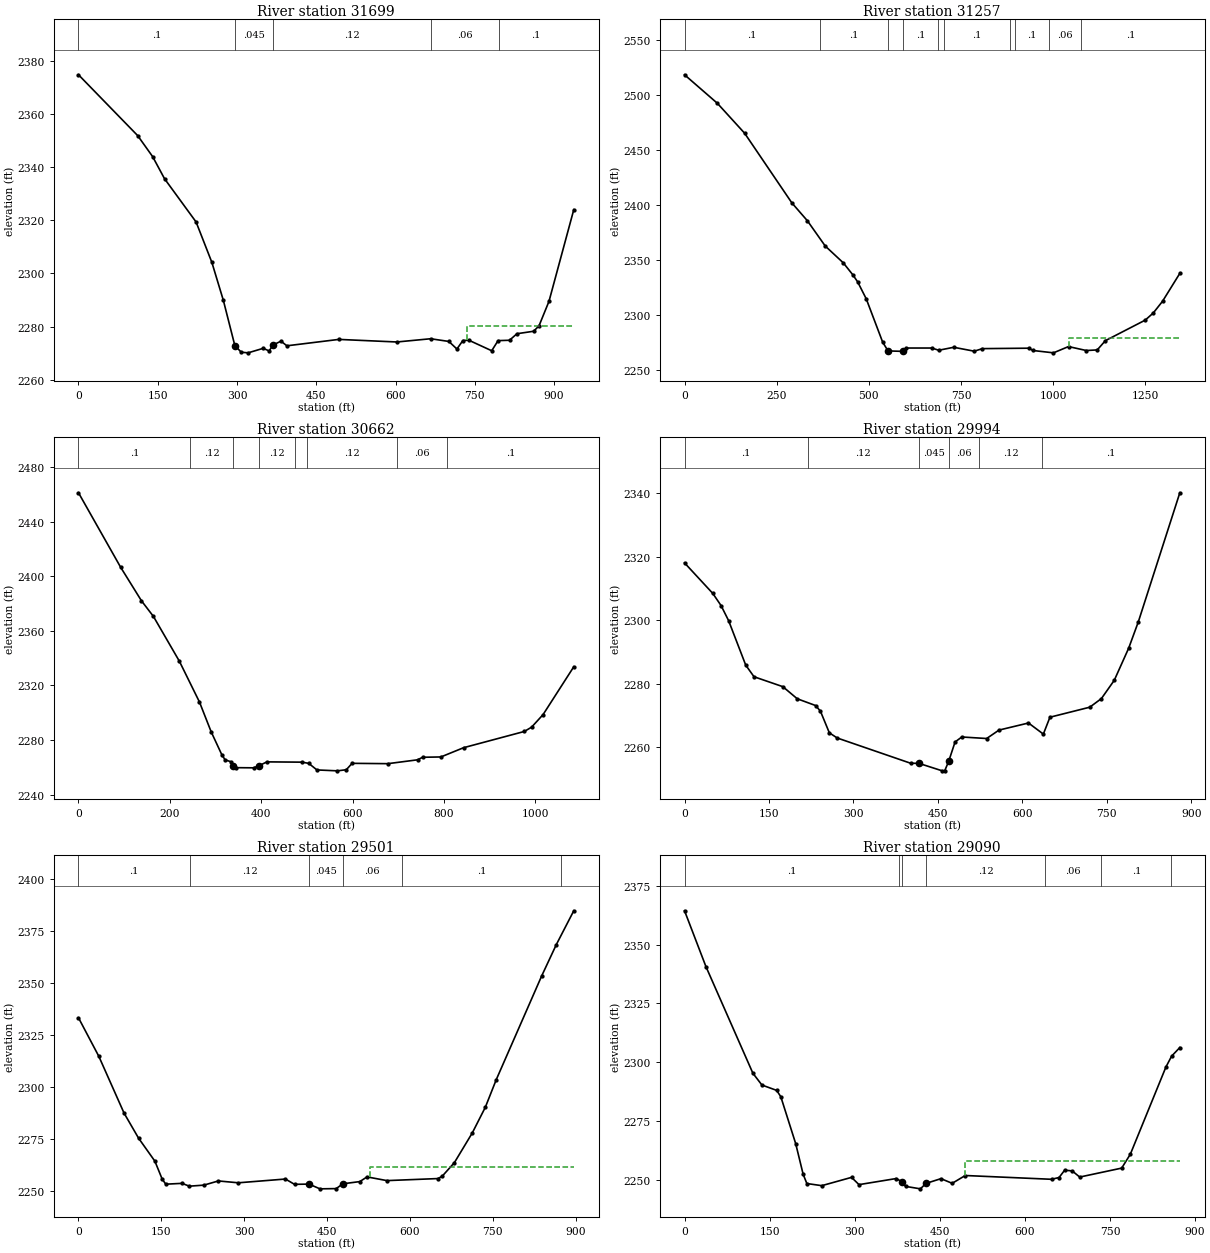
Type RM Length L Ch R = 1 ,31699   ,437.7,441.4,445.2
XS GIS Cut Line= 3
 2228025.1905138377112.9804166412227659.56558889377311.939008221
2227208.52384005377572.355482146
#Sta/Elev= 30
       0 2374.84     112 2351.92   140.3 2344.01   162.8 2335.68   222.5 2319.39
   252.3  2304.2   274.1 2289.86   295.8 2272.85   307.9 2270.34   320.9  2270.1
   349.5  2271.8   360.7 2270.82   368.1 2273.05   383.1  2274.5   394.3 2272.75
   492.5 2275.16   602.3 2274.19   666.3 2275.41   700.8 2274.39     716 2271.54
   727.3 2274.74   738.6 2274.85   781.8 2270.89   793.9  2274.7   815.5 2274.84
   829.6  2277.3   861.1 2278.23   871.3 2280.26   890.2  2289.5   937.1 2324.02
#Mann= 5 ,-1 , 0
       0      .1       0   295.8    .045       0   368.1     .12       0
  666.08     .06       0  794.87      .1       0
#XS Ineff= 2 , 0
                          734.58         2280.35
Permanent Ineff=
       F       F
Bank Sta=295.8,368.1
XS Rating Curve= 0 ,0
Exp/Cntr=0.3,0.1

Type RM Length L Ch R = 1 ,31257   ,596.6,595.9,596.4
XS GIS Cut Line= 2
2228095.40559646376605.8006567212226906.44045472377231.730507225
#Sta/Elev= 30
       0  2518.5    88.8 2492.64     163 2465.33   291.1 2401.97   333.4 2385.64
   381.7  2362.7   430.6 2347.43   455.9 2336.79   469.5 2330.19     493 2314.62
   537.6 2275.17   552.1 2267.28   593.4 2266.86   600.7  2269.9   670.9 2269.91
   689.5 2267.89   730.3 2270.58   785.9 2267.03   808.1 2269.36   934.2 2269.76
   945.3 2267.66  1000.9 2265.53  1041.7 2271.24  1089.9 2267.64  1119.6 2268.18
  1141.8 2276.62  1249.8 2295.29  1271.6 2301.77  1296.8 2312.45  1343.7 2337.82
#Mann= 10 ,-1 , 0
       0      .1       0  366.82      .1       0   552.1    .045       0
   593.4      .1       0  686.69      .1       0  704.11      .1       0
  883.35     .12       0  896.25      .1       0  988.12     .06       0
 1075.08      .1       0
#XS Ineff= 2 , 0
                         1042.67          2279.4
Permanent Ineff=
       F       F
Bank Sta=552.1,593.4
XS Rating Curve= 0 ,0
Exp/Cntr=0.3,0.1

Type RM Length L Ch R = 1 ,30662   ,668.9,667.9,660.3
XS GIS Cut Line= 3
2227514.77388372376229.6472095552227135.60699114 376468.18872723
2226601.23207563376814.022353143
#Sta/Elev= 30
       0 2461.37    92.3 2406.73   137.9 2382.12   164.1 2370.65   220.9  2337.8
   264.9 2307.87   290.6 2285.95     314 2269.08   321.1 2265.44     333 2264.15
   337.8 2261.21   344.8 2259.72   383.7  2259.6   394.9 2261.12   412.7 2263.97
   489.9 2263.76   504.2 2262.86   522.1 2258.05   566.8 2257.39   586.4 2258.19
   599.1  2262.9   677.4 2262.65   742.7 2265.49   753.3 2267.34   793.5 2267.58
   843.4 2274.38   976.3 2286.28   992.2 2289.46  1017.3 2298.66  1084.5 2333.73
#Mann= 8 ,-1 , 0
       0      .1       0  244.61     .12       0   337.8    .045       0
   394.9     .12       0  475.17      .1       0  499.95     .12       0
  697.94     .06       0  807.01      .1       0
Bank Sta=337.8,394.9
XS Rating Curve= 0 ,0
Exp/Cntr=0.3,0.1

Type RM Length L Ch R = 1 ,29994   ,470.3,492.8,510.6
XS GIS Cut Line= 4
2226905.39879014375794.2304294712226810.60731305375985.897040889
2226593.94042355376172.3556574732226290.81537364376401.522193894
#Sta/Elev= 30
       0 2317.99    50.2 2308.38    64.8 2304.58    78.2 2299.85   108.7 2285.82
   123.4 2282.17   174.6 2279.05   200.2 2275.24   232.7 2273.12   241.3 2271.36
   257.2 2264.53   271.1 2262.91   401.4 2254.97   416.4 2254.92   457.7 2252.57
   462.1 2252.59   469.12255.538   480.5 2261.65   492.4 2263.22   536.6 2262.74
   558.5 2265.39   610.9 2267.62   637.3 2264.13     649 2269.44   719.7 2272.59
   740.4  2275.3   763.3 2281.07   788.9 2291.18     806 2299.45   879.7 2340.05
#Mann= 6 ,-1 , 0
       0      .1       0  218.63     .12       0   416.4    .045       0
   469.1     .06       0  523.14     .12       0   635.5      .1       0
Bank Sta=416.4,469.1
XS Rating Curve= 0 ,0
Exp/Cntr=0.3,0.1

Type RM Length L Ch R = 1 ,29501   ,409.8,411.1,411.8
XS GIS Cut Line= 3
2226868.94052972375729.6472253052226342.89893089375744.230529472
2225974.14868414375777.563796148
#Sta/Elev= 30
       0 2333.36    36.8 2314.82    82.5 2287.47   108.7 2275.44   138.3 2264.34
   151.4 2255.76     158 2253.27   187.5 2253.67   200.6 2252.31   226.9 2252.81
   253.2 2254.83   289.3 2253.94   374.6 2255.75     391  2253.2   417.3 2253.31
     437 2251.03   466.5 2251.14   478.5 2253.46   509.2 2254.52   522.3 2256.78
   558.3 2254.99   650.7 2255.98   658.4 2257.13   680.4 2263.64   712.8 2277.94
   736.4  2290.3   756.2  2303.6   838.5 2353.57   864.9  2368.6   896.5 2384.88
#Mann= 6 ,-1 , 0
       0      .1       0  202.03     .12       0   417.3    .045       0
   478.5     .06       0  585.16      .1       0  873.29      .1       0
#XS Ineff= 2 , 0
                          527.45         2261.71
Permanent Ineff=
       F       F
Bank Sta=417.3,478.5
XS Rating Curve= 0 ,0
Exp/Cntr=0.3,0.1

Type RM Length L Ch R = 1 ,29090   ,561.7,551.1,532
XS GIS Cut Line= 3
2226874.14885263375332.7723628882226436.64874339375337.980685815
2226004.35728514375391.105579555
#Sta/Elev= 30
       0 2364.38    37.7 2340.64   120.5 2295.26   136.4 2290.25   162.4 2287.97
   169.7 2285.27   195.9 2265.35   209.1 2252.27   215.6 2248.35   241.9 2247.44
   294.4 2250.97   307.5 2247.88   373.1 2250.47   382.9 2249.14   389.7 2247.13
   415.8 2246.09   425.6  2248.4     452 2250.42   471.8 2248.44   494.9 2251.76
     647 2250.15   660.2 2250.91   670.1 2254.03   683.4 2253.72   696.6  2251.1
   770.6 2254.91   785.8 2260.79   848.6 2297.92   858.6 2302.53   873.1 2306.21
#Mann= 7 ,-1 , 0
       0      .1       0  378.37     .12       0   382.9    .045       0
   425.6     .12       0  635.42     .06       0  734.82      .1       0
  858.18      .1       0
#XS Ineff= 2 , 0
                          494.06         2258.12
Permanent Ineff=
       F       F
Bank Sta=382.9,425.6
XS Rating Curve= 0 ,0
Exp/Cntr=0.3,0.1

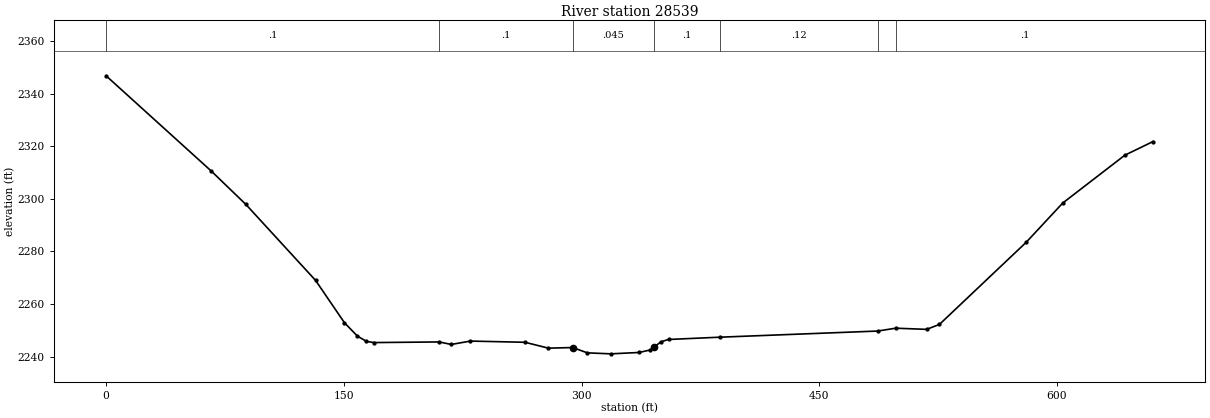
Type RM Length L Ch R = 1 ,28539   ,516.6,489.7,445.4
XS GIS Cut Line= 3
2226458.52369964374718.1889463962226184.56558613374962.980451554
2225962.69037372375154.647062972
#Sta/Elev= 30
       0 2346.74    66.2 2310.64    88.2 2297.87   132.2 2268.99   150.4 2252.92
   158.6 2247.83   164.3 2245.83     169 2245.38   210.2 2245.62   217.8 2244.67
   229.9 2245.95   264.3 2245.49   279.1 2243.26   294.4 2243.49   303.7 2241.47
   318.5  2241.1   336.3 2241.62   343.1 2242.54   345.6  2243.6   350.2 2245.71
   354.9 2246.56   387.1 2247.42   486.8 2249.76   498.2 2250.84   517.7  2250.4
   525.8 2252.27   580.5 2283.45   603.6 2298.39   642.8 2316.57   660.6 2321.76
#Mann= 7 ,-1 , 0
       0      .1       0   210.2      .1       0   294.4    .045       0
   345.6      .1       0   387.1     .12       0   486.8     .06       0
   498.2      .1       0
Bank Sta=294.4,345.6
XS Rating Curve= 0 ,0
Exp/Cntr=0.5,0.3