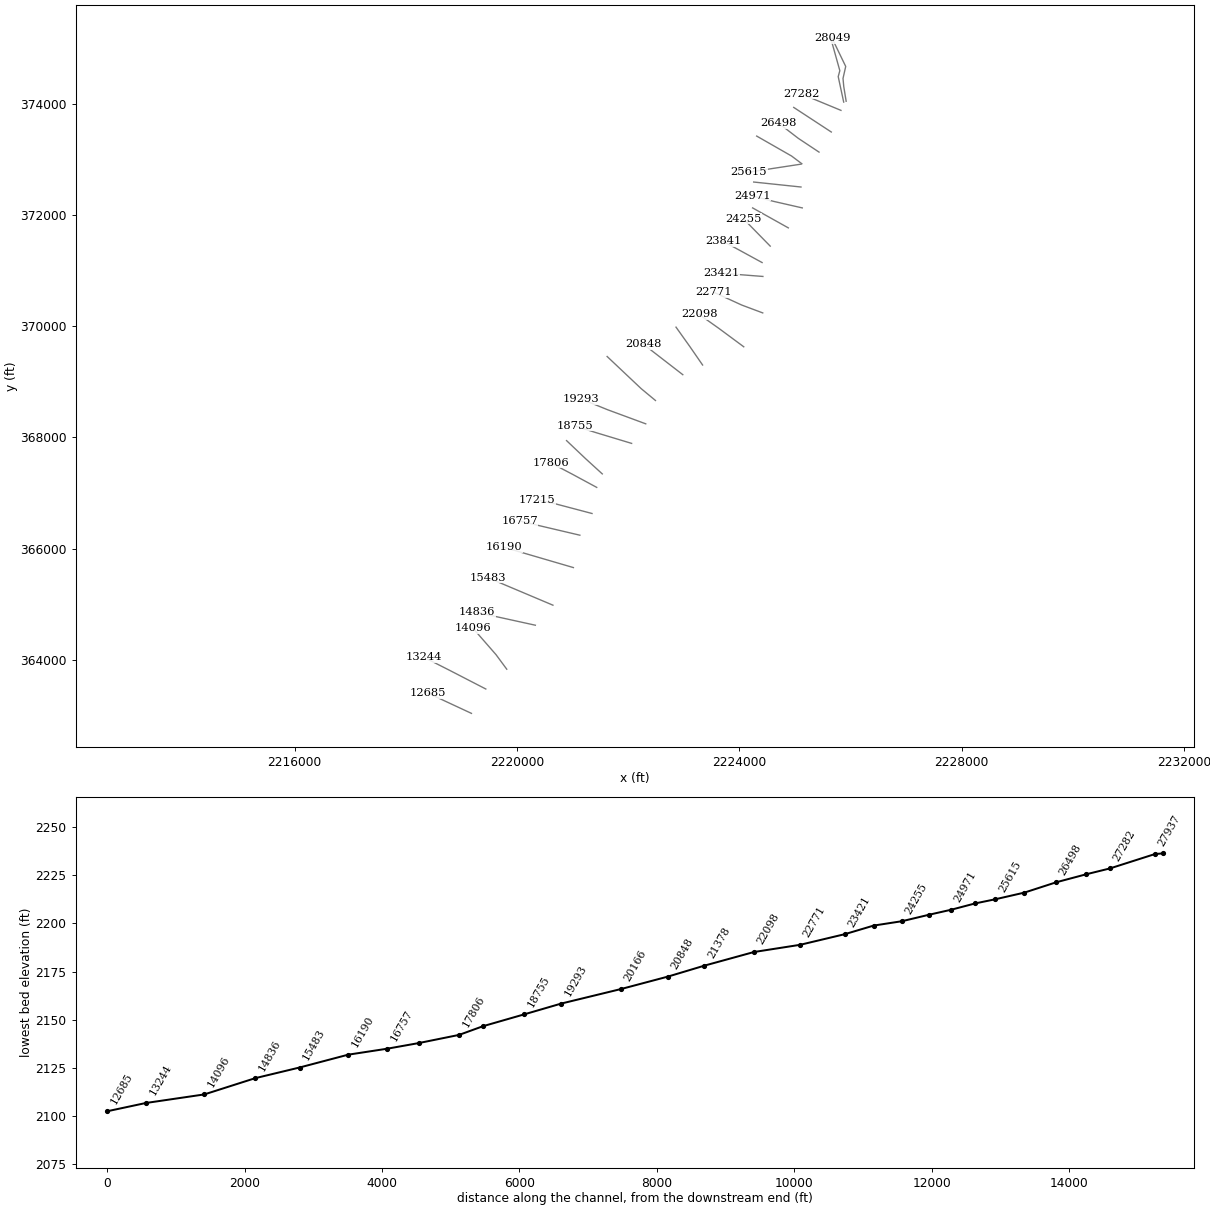
HEC-RAS study NFANTNYCK.prj: NFANTNYCK

--- NFANTNYCK.g01 (geometry) --- (continued)

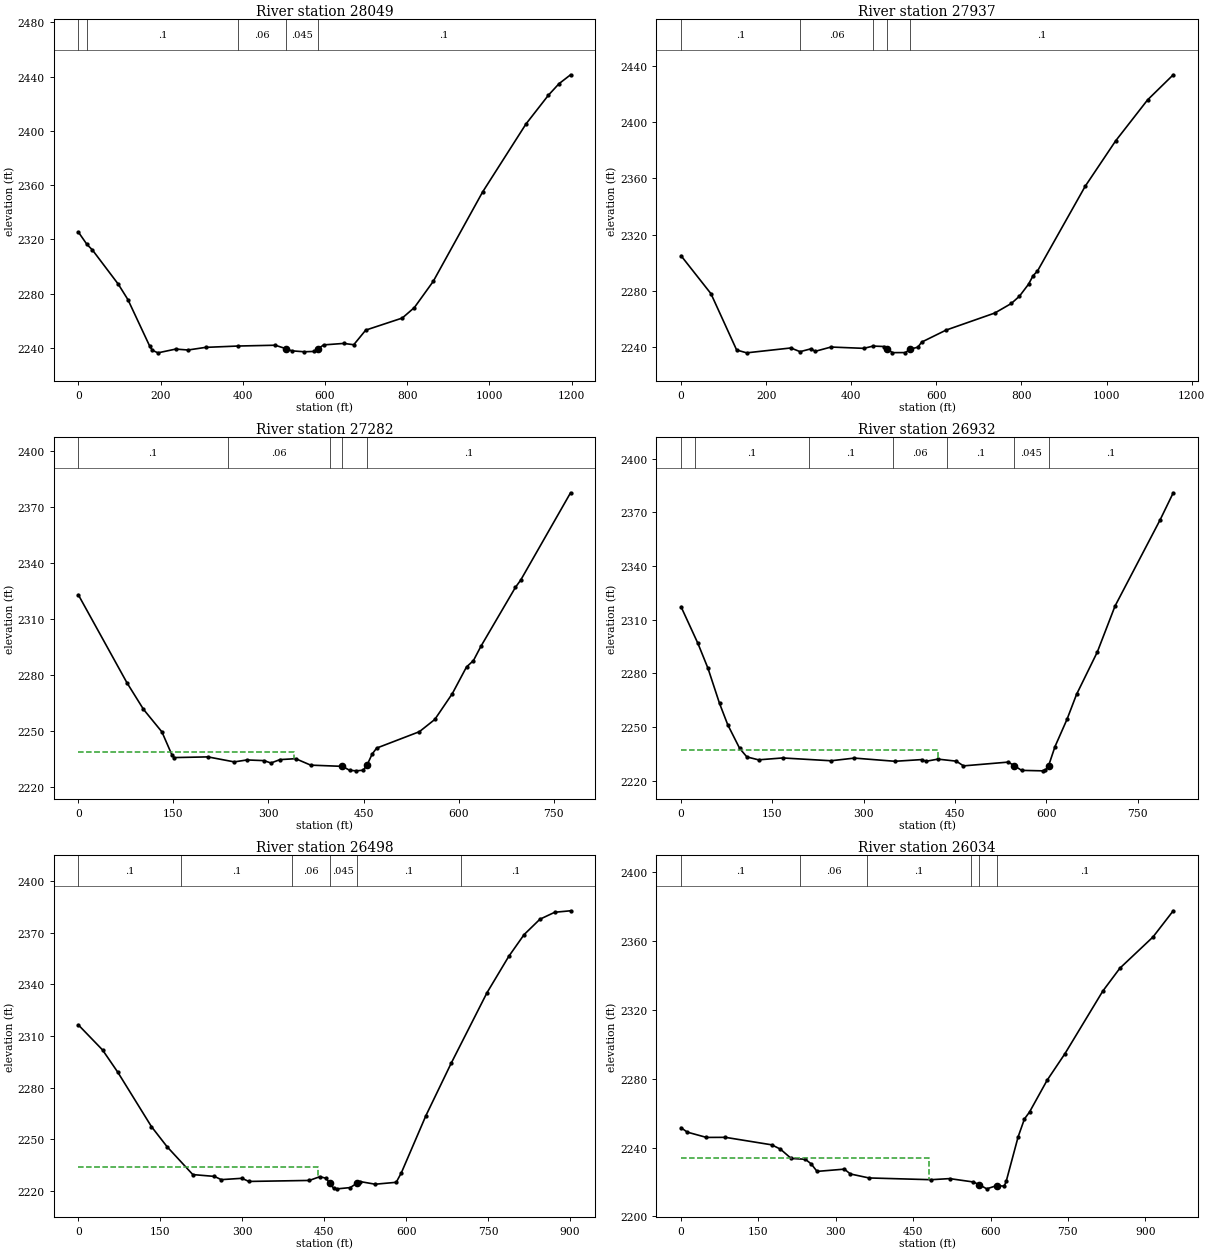
Type RM Length L Ch R = 1 ,28049   ,110.7,111.5,124
XS GIS Cut Line= 5
2225923.84104197374050.2060303992225880.22137855374317.827542394
2225867.24371421374460.9696445612225915.85483748374676.247429222
 2225671.0633323375182.150288805
#Sta/Elev= 30
       0 2325.41      21 2316.28    34.2 2312.23    97.3 2286.93   120.6 2275.62
   173.8 2241.21   180.4  2238.2   193.7 2236.38     237 2239.15   266.9 2238.47
   309.7 2240.41   388.8  2241.4   479.1 2241.99     506 2239.35   519.4 2237.86
   549.7 2237.16   573.2 2237.42     583 2239.33   596.8 2242.23   645.6 2243.32
   670.1 2242.36   699.2 2253.12   788.1 2262.02   817.6 2269.76   863.3 2288.98
   983.5 2354.88  1089.2 2405.09  1143.9 2426.34  1169.4 2434.72  1197.6 2441.32
#Mann= 5 ,-1 , 0
       0      .1       0      21      .1       0   388.8     .06       0
     506    .045       0     583      .1       0
#XS Ineff= 2 , 0
             466  2239.2     623          2239.2
Permanent Ineff=
       F       F
Bank Sta=506,583
XS Rating Curve= 0 ,0
Exp/Cntr=0.5,0.3

Type RM Length L Ch R = 1 ,27937   ,612.1,655.8,681.5
XS GIS Cut Line= 4
2225879.39657706 374034.92817381 2225780.7855538 374493.26157473
2225809.95216213374600.2059146462225654.39669897375155.761562064
#Sta/Elev= 30
       0 2305.06    70.3 2278.09   130.7 2238.07   154.2 2236.06   258.1 2239.52
   279.7 2236.89   305.2 2238.91   315.3 2237.14   352.4 2240.18   429.4 2239.25
   451.4 2240.86   476.8 2240.56   484.3 2238.92   496.8  2236.2   527.4 2236.25
   537.7  2238.6   537.7 2238.61   556.4 2240.08   565.6 2243.71   622.7  2252.2
   737.2 2264.33   776.1 2271.12   795.3 2276.33   816.6 2284.83   827.3  2290.9
   837.4 2294.07   949.6 2354.34  1021.1 2386.58  1096.3 2415.75  1156.6 2433.58
#Mann= 5 ,-1 , 0
       0      .1       0   279.7     .06       0   451.4      .1       0
   484.3    .045       0   537.7      .1       0
Bank Sta=484.3,537.7
XS Rating Curve= 0 ,0
Exp/Cntr=0.5,0.3

Type RM Length L Ch R = 1 ,27282   ,352.9,349.7,350.7
XS GIS Cut Line= 2
2225830.39897163373885.8973038942225112.69043331374182.772366315
#Sta/Elev= 30
       0 2323.02    76.6  2275.9   102.8 2261.59   131.9 2249.47   147.6 2237.19
   151.2 2235.71   204.5 2236.07     246 2233.39   266.1 2234.43   293.2 2234.07
   303.9 2232.78   318.1 2234.61   342.9 2235.11   366.6 2231.65   416.8 2230.99
   428.1 2228.87   438.8 2228.59   449.5 2228.94   455.5 2231.64   463.6 2237.57
   470.7 2240.79   538.2  2249.6   562.5 2256.17   590.1    2270   612.5 2284.32
   623.4 2287.72   635.3 2295.44   689.8 2327.09     698 2330.91   776.7 2377.77
#Mann= 5 ,-1 , 0
       0      .1       0  235.42     .06       0  396.59      .1       0
   416.8    .045       0   455.5      .1       0
#XS Ineff= 2 , 0
          340.46 2238.89
Permanent Ineff=
       F       F
Bank Sta=416.8,455.5
XS Rating Curve= 0 ,0
Exp/Cntr=0.3,0.1

Type RM Length L Ch R = 1 ,26932   ,434.8,434.3,432.6
XS GIS Cut Line= 2
2225656.44033006373496.3137654812224980.39870314373939.022197649
#Sta/Elev= 30
       0 2317.21    27.7 2296.72    44.3 2282.75    63.2 2263.19    76.7 2251.25
    96.3 2238.02   108.1 2233.29   127.2 2231.66   166.9 2232.71   246.2 2231.14
   284.6 2232.63   351.2 2230.85     395 2231.79   402.2 2230.85   421.8 2232.05
   451.9 2230.92   463.7 2228.28   537.2 2230.39   546.7 2228.48   559.1 2225.77
   593.5 2225.51   598.3 2225.92   603.5 2228.44     614  2239.1   633.6 2254.22
   649.3 2268.19   683.4 2291.87   712.5 2317.56   786.5  2365.7   808.1 2380.85
#Mann= 7 ,-1 , 0
       0      .1       0   22.43      .1       0  209.98      .1       0
  348.62     .06       0   436.6      .1       0   546.7    .045       0
   603.5      .1       0
#XS Ineff= 2 , 0
          422.18 2237.41
Permanent Ineff=
       F       F
Bank Sta=546.7,603.5
XS Rating Curve= 0 ,0
Exp/Cntr=0.3,0.1

Type RM Length L Ch R = 1 ,26498   ,462.4,463.3,455.8
XS GIS Cut Line= 3
2225435.60711031373134.8554988952225063.73219788373381.730661318
2224703.31559588373658.813768566
#Sta/Elev= 30
       0 2316.44    44.3 2301.92    72.3 2288.96   133.8 2257.47   162.2 2245.89
   209.5 2229.65   249.1 2228.59   261.6 2226.71   299.5 2227.49   312.1 2225.67
   422.8 2226.25     442 2228.42   453.2 2227.54   460.3 2224.64   467.3 2221.66
   474.3 2221.38   497.7 2222.11  510.062224.672   516.3 2225.56   543.4 2224.06
   581.9 2225.17   591.3 2230.71   636.3 2263.88   682.5 2294.22     748 2335.07
   787.8 2356.13   815.9 2368.77   844.9  2377.7     872 2381.74     901  2382.6
#Mann= 6 ,-1 , 0
       0      .1       0  187.73      .1       0  391.93     .06       0
   460.3    .045       0  510.06      .1       0  701.07      .1       0
#XS Ineff= 2 , 0
           438.6 2234.25
Permanent Ineff=
       F       F
Bank Sta=460.3,510.06
XS Rating Curve= 0 ,0
Exp/Cntr=0.3,0.1

Type RM Length L Ch R = 1 ,26034   ,406.2,419.6,431.5
XS GIS Cut Line= 3
2225126.23207289372925.4805895542224941.85711356373064.022307232
2224313.73205747373423.397244647
#Sta/Elev= 30
       0 2251.56    12.1 2248.99    49.3 2245.91      86 2245.96   175.9  2241.6
   192.7  2239.1   213.5 2233.69     241 2233.21   252.4  2230.5   263.7 2226.16
   316.6 2227.47   328.3 2224.67   364.4 2222.35   484.6 2221.33   520.8 2221.97
   566.7 2220.01   578.4 2218.39   592.8 2216.02     612 2217.91   626.6 2217.56
   630.4 2220.34   653.6 2246.29   665.8 2256.66   675.7  2260.7   709.7 2279.12
   744.3 2294.59   817.8 2331.03   850.8 2344.28     915 2362.43   954.3 2377.67
#Mann= 6 ,-1 , 0
       0      .1       0  231.45     .06       0   360.3      .1       0
  562.76      .1       0   578.4    .045       0     612      .1       0
#XS Ineff= 2 , 0
          480.48 2233.92
Permanent Ineff=
       F       F
Bank Sta=578.4,612
XS Rating Curve= 0 ,0
Exp/Cntr=0.3,0.1

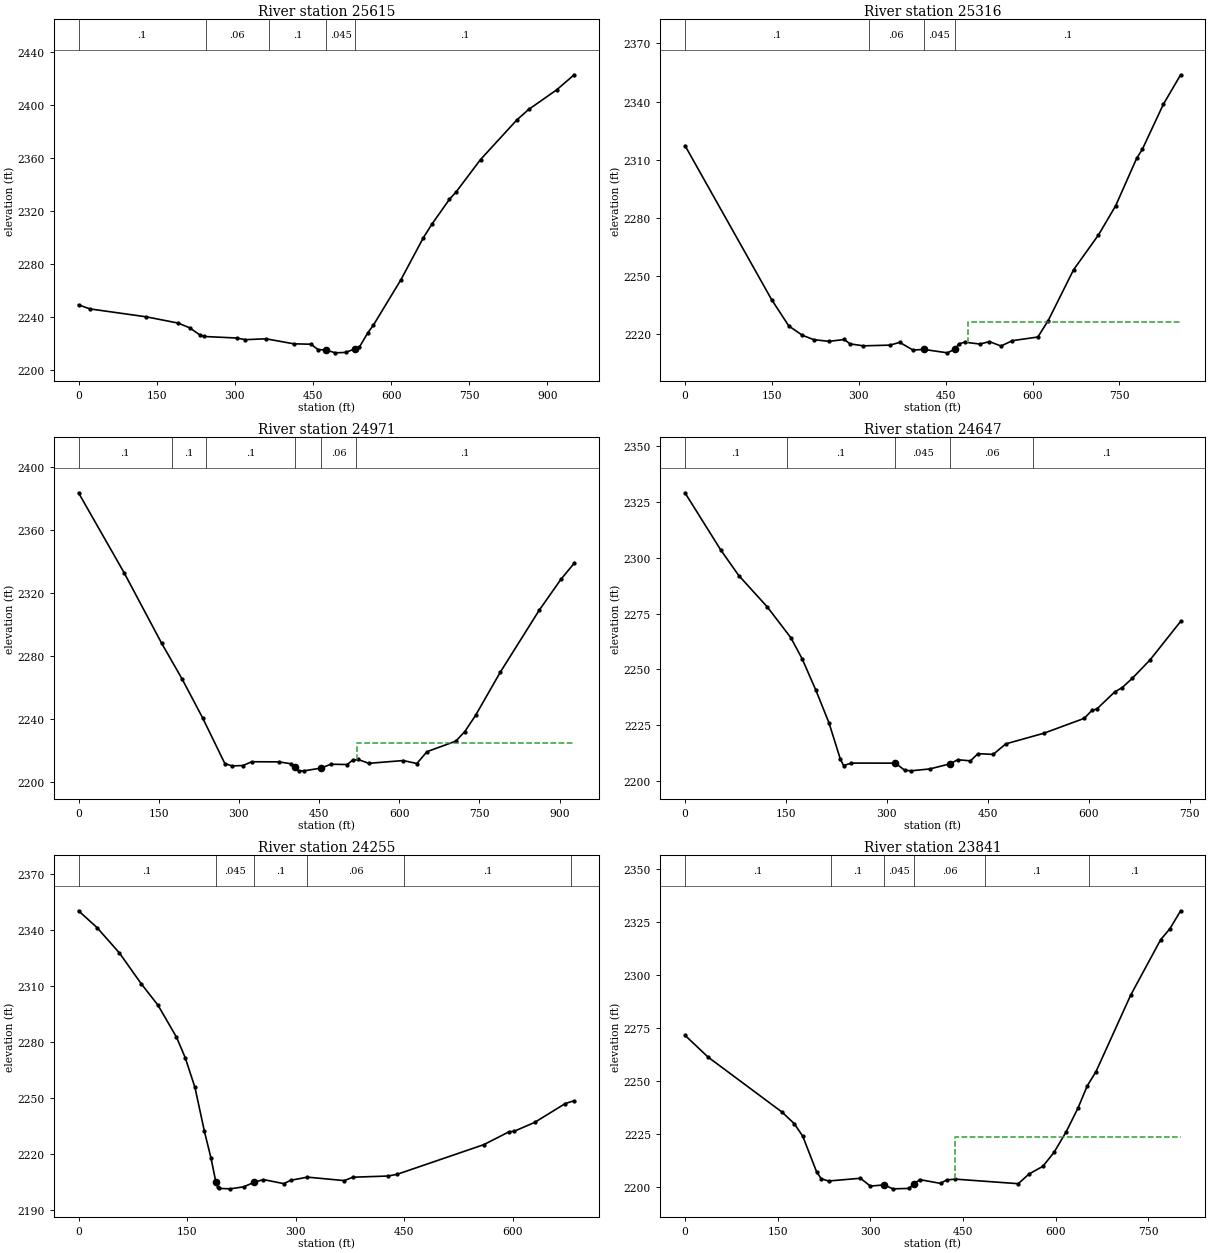
Type RM Length L Ch R = 1 ,25615   ,303,298.6,289.5
XS GIS Cut Line= 2
2225111.64876872 372918.188937472224171.02368148372774.438896894
#Sta/Elev= 30
       0 2248.86    21.6 2245.77   130.1 2239.77   190.9 2235.08   213.6 2231.44
   233.7 2225.89   240.7 2224.93   303.7 2223.78   320.3 2222.53   359.8 2223.19
   413.2  2219.4   446.4 2219.09   459.7 2215.07   475.6 2214.73   492.8 2212.59
     513 2212.92   530.3 2215.58   539.4 2217.06   555.6 2227.84   565.9  2233.4
     619 2267.81   662.2 2299.63   678.8 2309.91   711.9  2328.4   725.2 2334.19
   771.7 2358.46   841.6 2388.43   864.2  2396.3   917.7 2411.01   951.5 2422.45
#Mann= 5 ,-1 , 0
       0      .1       0  243.96     .06       0  364.98      .1       0
   475.6    .045       0   530.3      .1       0
Bank Sta=475.6,530.3
XS Rating Curve= 0 ,0
Exp/Cntr=0.3,0.1

Type RM Length L Ch R = 1 ,25316   ,344.7,344.9,339.1
XS GIS Cut Line= 2
2225111.12810047372506.7304428072224260.08616738372596.313925058
#Sta/Elev= 30
       0 2317.32   149.6 2237.83   179.3 2224.24   202.4  2219.5   222.2  2217.2
   248.6 2216.31     275 2217.28   284.9 2215.02     308    2214   354.1 2214.37
   370.6  2215.8   393.7 2211.81   412.2 2212.16   453.1 2210.39   466.3 2212.35
   472.9    2215   482.8  2215.9   509.2 2214.92   525.7 2216.19   545.5 2213.91
   565.3 2216.68   609.2 2218.55   627.1 2227.05   670.8 2253.22   713.9 2271.23
   743.5 2286.24   779.7 2310.68   789.6  2315.4   825.9 2338.62   855.7 2353.83
#Mann= 4 ,-1 , 0
       0      .1       0  317.14     .06       0   412.2    .045       0
   466.3      .1       0
#XS Ineff= 2 , 0
                          487.83         2226.33
Permanent Ineff=
       F       F
Bank Sta=412.2,466.3
XS Rating Curve= 0 ,0
Exp/Cntr=0.3,0.1

Type RM Length L Ch R = 1 ,24971   ,329.1,323.9,314.4
XS GIS Cut Line= 3
2225134.04472131372130.6888720542224622.58642663372247.355633482
2224233.00288822372348.397098064
#Sta/Elev= 30
       0  2383.8    85.3    2333   155.3 2288.31   193.7 2265.54   232.1 2240.82
   273.7 2211.77   287.2 2210.28   307.4 2210.52   324.2 2212.93   374.7 2212.85
   398.2 2211.61   404.7 2209.33   411.7 2207.16   421.8 2207.15   453.3 2208.87
   472.2 2211.36   502.5 2211.15   512.6 2213.89   522.7 2214.38     543 2211.93
   607.4 2213.68   632.9 2211.79   651.7 2219.32   705.6    2226   722.7 2232.14
   742.7 2242.42     789 2269.87   861.6 2309.13   902.3 2328.81   927.1 2339.02
#Mann= 6 ,-1 , 0
       0      .1       0   174.7      .1       0  239.02      .1       0
   404.7    .045       0   453.3     .06       0  519.18      .1       0
#XS Ineff= 2 , 0
                          521.79         2224.87
Permanent Ineff=
       F       F
Bank Sta=404.7,453.3
XS Rating Curve= 0 ,0
Exp/Cntr=0.3,0.1

Type RM Length L Ch R = 1 ,24647   ,397.7,392.4,385.4
XS GIS Cut Line= 2
2224883.00290056371771.313934639 2224240.2945403372130.688872054
#Sta/Elev= 30
       0 2329.13      53 2303.57    79.9 2292.06   122.3 2277.98   157.2 2264.23
   174.1 2254.73   194.6 2240.57   213.9 2226.08   230.7  2209.9   235.6 2206.92
   247.4 2208.01   312.7 2207.99   326.3 2204.84   335.4 2204.54   363.9  2205.4
     394  2207.7   405.3 2209.53   424.1    2209   435.3 2212.23   457.9 2211.91
   476.6 2216.62   533.1 2221.38   593.2 2228.06   604.5 2231.59     612 2232.28
   638.3 2239.86   649.6 2241.84   664.8 2246.07     691 2254.26   736.4  2271.5
#Mann= 5 ,-1 , 0
       0      .1       0  150.93      .1       0   312.7    .045       0
     394     .06       0  517.24      .1       0
Bank Sta=312.7,394
XS Rating Curve= 0 ,0
Exp/Cntr=0.3,0.1

Type RM Length L Ch R = 1 ,24255   ,405.9,413.8,419.7
XS GIS Cut Line= 2
 2224556.9612298371443.1889347292224077.79453722371932.772273138
#Sta/Elev= 30
       0 2350.38    25.5 2341.39    56.5 2327.77    86.5 2311.31   109.7  2299.8
   135.4  2282.6   147.5 2271.51   160.9 2255.66     174 2232.01   183.2 2217.52
   189.7 2205.06   192.4 2202.23   194.4 2201.43   209.6 2201.19   228.2 2202.26
   242.9 2204.73   255.4 2206.16   283.8 2203.98   293.1 2205.75   316.3 2207.47
   367.4  2205.6     379 2207.43   427.7 2208.06   440.3 2208.98   560.2 2224.91
   594.7 2231.75   602.5 2232.14   630.6 2236.88   672.8 2246.97     685 2248.45
#Mann= 6 ,-1 , 0
       0      .1       0   189.7    .045       0   242.9      .1       0
  315.73     .06       0  450.13      .1       0  680.57      .1       0
Bank Sta=189.7,242.9
XS Rating Curve= 0 ,0
Exp/Cntr=0.3,0.1

Type RM Length L Ch R = 1 ,23841   ,410.7,419.9,429.7
XS GIS Cut Line= 2
2224411.12786005371147.3555368932223706.96128939371531.730424315
#Sta/Elev= 30
       0 2271.45    37.3 2261.16     157 2235.18   176.7 2229.74   190.6 2223.78
     213 2206.95   220.5  2203.7   232.3 2202.61     284 2203.91     300 2200.21
   322.3 2200.77   336.4 2198.91   362.5 2199.11     370 2200.99   379.8 2203.28
   413.6 2201.48   423.3 2203.09   437.3  2203.5   539.4 2201.34   556.9 2205.93
   579.3 2209.56   597.4 2216.19   616.8 2225.77   636.1 2237.07     651 2247.52
   665.3 2254.33   721.4 2290.43   769.9 2316.61   784.9 2321.79   802.2 2330.25
#Mann= 6 ,-1 , 0
       0      .1       0  237.13      .1       0   322.3    .045       0
     370     .06       0   486.3      .1       0  653.16      .1       0
#XS Ineff= 2 , 0
                          436.33         2223.22
Permanent Ineff=
       F       F
Bank Sta=322.3,370
XS Rating Curve= 0 ,0
Exp/Cntr=0.3,0.1

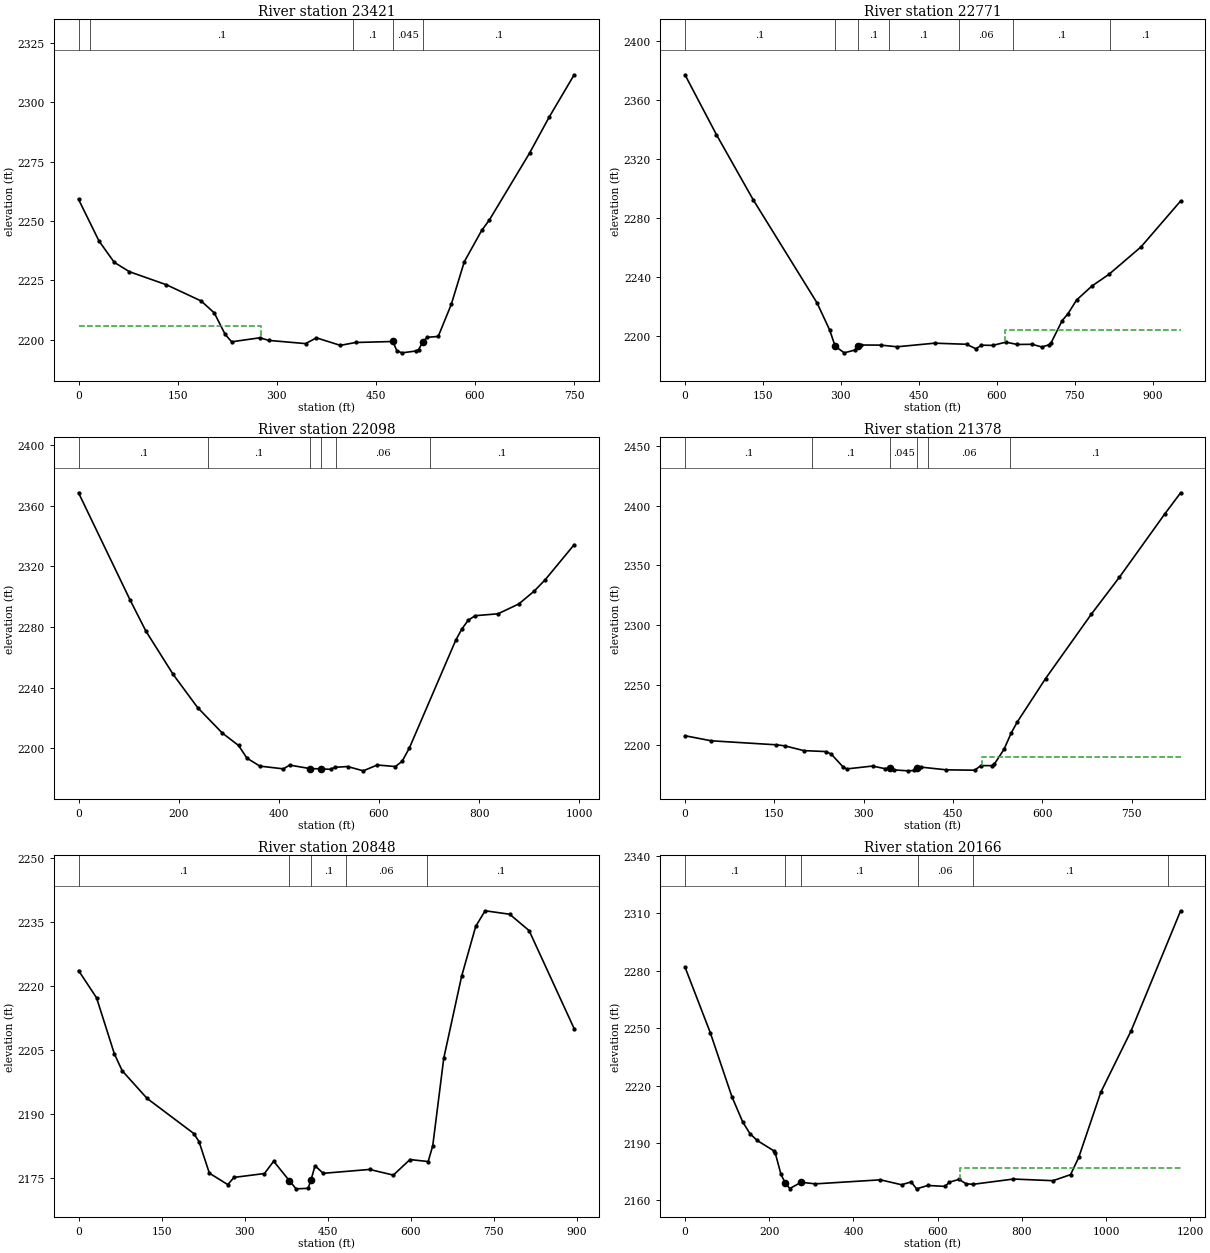
Type RM Length L Ch R = 1 ,23421   ,651.4,650.2,639.1
XS GIS Cut Line= 2
2224425.71116422370897.3553807292223677.79468106370955.688925475
#Sta/Elev= 30
       0 2259.17      31  2241.6    54.1 2232.59    77.1 2228.64   133.1 2223.14
   185.7  2216.3   205.5 2211.28   221.9 2202.26   231.8  2199.1   274.6  2200.8
   287.7  2199.7   343.7 2198.34   360.1 2200.77   396.3  2197.6   419.4 2198.81
   475.7 2199.23   481.9 2195.31   489.6 2194.45   511.5 2195.25   514.8 2195.81
   521.1 2199.12     528 2201.01   544.4 2201.35   564.2 2214.87   583.9 2232.86
   610.2 2246.03   621.9 2250.48   682.6 2278.59   712.2 2293.73   750.2 2311.65
#Mann= 5 ,-1 , 0
       0      .1       0   17.87      .1       0  415.18      .1       0
   475.7    .045       0   521.1      .1       0
#XS Ineff= 2 , 0
          276.63 2205.68
Permanent Ineff=
       F       F
Bank Sta=475.7,521.1
XS Rating Curve= 0 ,0
Exp/Cntr=0.3,0.1

Type RM Length L Ch R = 1 ,22771   ,677.1,673.2,662.3
XS GIS Cut Line= 3
2224422.58617046370241.1053808932224044.46127056370382.772092313
2223544.46128631370611.938956812
#Sta/Elev= 30
       0 2376.93    60.6 2336.41   131.3 2292.41   254.3 2222.59   278.5  2204.3
     289 2193.38   306.5 2188.93   327.5 2190.87   333.3 2193.26     338 2194.22
   376.6 2194.15   408.2 2193.03   480.4 2195.46   541.8 2194.72   559.8 2191.67
   570.6  2194.1   592.3 2193.97   617.6 2196.16   639.2  2194.6   668.1 2194.69
   686.8 2192.89   700.6 2194.37   704.4 2195.61   725.8 2210.73   736.7 2215.17
   753.6 2224.66   783.3 2234.16   816.1 2242.06   877.6 2260.58   953.8  2291.6
#Mann= 7 ,-1 , 0
       0      .1       0     289    .045       0   333.3      .1       0
  392.88      .1       0  528.08     .06       0  631.11      .1       0
  818.67      .1       0
#XS Ineff= 2 , 0
                           616.3         2204.33
Permanent Ineff=
       F       F
Bank Sta=289,333.3
XS Rating Curve= 0 ,0
Exp/Cntr=0.3,0.1

Type RM Length L Ch R = 1 ,22098   ,716,719.8,715.1
XS GIS Cut Line= 3
2224080.91953097369631.7306153922223633.00310397369962.980609059
2223279.87782598370212.980437145
#Sta/Elev= 30
       0 2368.52   103.4 2297.56   134.6 2277.31   189.1 2248.71   237.8 2226.92
     287 2210.14   319.7 2201.89   336.3 2193.56   362.1  2188.3   409.1 2186.49
   421.7 2188.97  462.162186.662  484.422186.468   503.3 2186.18   511.5 2187.49
   537.4 2188.02   568.6 2185.18   596.6 2189.03   632.7 2188.01   646.3 2191.48
   660.9 2200.38   753.3  2271.3   765.4 2278.63   778.1 2284.45   792.2 2287.48
   837.7 2288.72   879.3 2295.23   909.9 2303.65   932.3 2311.32   989.8  2334.3
#Mann= 6 ,-1 , 0
       0      .1       0  259.18      .1       0  462.16    .045       0
  484.42      .1       0  514.69     .06       0  701.66      .1       0
Bank Sta=462.16,484.42
XS Rating Curve= 0 ,0
Exp/Cntr=0.3,0.1

Type RM Length L Ch R = 1 ,21378   ,524.3,529.7,535
XS GIS Cut Line= 3
2223340.29469989369303.6056154822223108.00284164369640.063932061
2222862.16967189 369984.85556531
#Sta/Elev= 30
       0 2207.48      44 2203.25   153.6 2199.88   167.6 2199.03   199.5 2195.03
   237.6 2194.22     246 2191.91   265.7 2181.25   271.3 2179.71   314.9 2182.12
   335.1 2180.02   343.5 2180.42     351 2178.88     375 2178.12   384.6 2178.44
   390.4 2180.22   396.1 2181.24   439.1 2178.95   486.8 2178.66   496.6  2182.5
   515.4 2182.47   519.7 2183.91   535.8  2196.2   547.9 2209.84   557.7 2218.75
   605.5  2255.3   682.4 2309.17   729.5 2340.04   805.7 2392.98   832.3 2410.66
#Mann= 6 ,-1 , 0
       0      .1       0  213.23      .1       0   343.5    .045       0
   390.4      .1       0  408.06     .06       0  545.91      .1       0
#XS Ineff= 2 , 0
                          498.59         2189.57
Permanent Ineff=
       F       F
Bank Sta=343.5,390.4
XS Rating Curve= 0 ,0
Exp/Cntr=0.3,0.1

Type RM Length L Ch R = 1 ,20848   ,680.5,682.6,678.2
XS GIS Cut Line= 2
2222984.04475622369129.6473019722222275.71119913369677.563857064
#Sta/Elev= 30
       0 2223.66    32.6 2217.26    64.7 2204.14    78.9 2200.15   123.7 2193.68
   208.4 2185.41   217.7 2183.54   236.4 2176.13   269.7 2173.44   280.9 2175.13
     336 2176.04   352.6 2178.93   381.1 2174.33   393.1 2172.45   414.8 2172.57
   420.2 2174.59   427.3 2177.86   442.2 2176.09   525.9    2177   568.8 2175.67
   598.9 2179.32   631.7 2178.85     640 2182.55   659.9 2203.09   692.1 2222.27
   717.6    2234   734.6 2237.67     779 2236.86   814.1 2233.02   895.5 2210.02
#Mann= 5 ,-1 , 0
       0      .1       0   381.1    .045       0   420.2      .1       0
  483.01     .06       0  628.82      .1       0
Bank Sta=381.1,420.2
XS Rating Curve= 0 ,0
Exp/Cntr=0.3,0.1

Type RM Length L Ch R = 1 ,20166   ,839.8,872.9,867.6
XS GIS Cut Line= 3
2222492.37808864368665.0639135542222235.08628039368878.605481222
2221622.58619305369456.730637312
#Sta/Elev= 30
       0 2281.93      60 2247.67   111.4 2214.16   137.1 2200.93   154.1 2194.91
   171.2  2191.3   211.6 2185.78     214 2184.96   227.9 2173.53  237.822169.142
   248.9 2166.16   275.8 2169.41   309.5 2168.59     464  2170.7     514 2168.14
     537 2169.59   549.7 2165.99   576.5 2167.75   617.4 2167.27   627.5 2169.48
   650.7 2170.93     667 2168.66   683.2 2168.35   779.8 2171.11   873.6 2170.25
   915.3 2173.41   934.7 2182.44   987.2 2216.54  1059.2 2248.68  1176.6 2311.35
#Mann= 6 ,-1 , 0
       0      .1       0  237.82    .045       0   275.8      .1       0
   553.1     .06       0  682.67      .1       0 1145.66      .1       0
#XS Ineff= 2 , 0
                          653.99         2177.09
Permanent Ineff=
       F       F
Bank Sta=237.82,275.8
XS Rating Curve= 0 ,0
Exp/Cntr=0.3,0.1

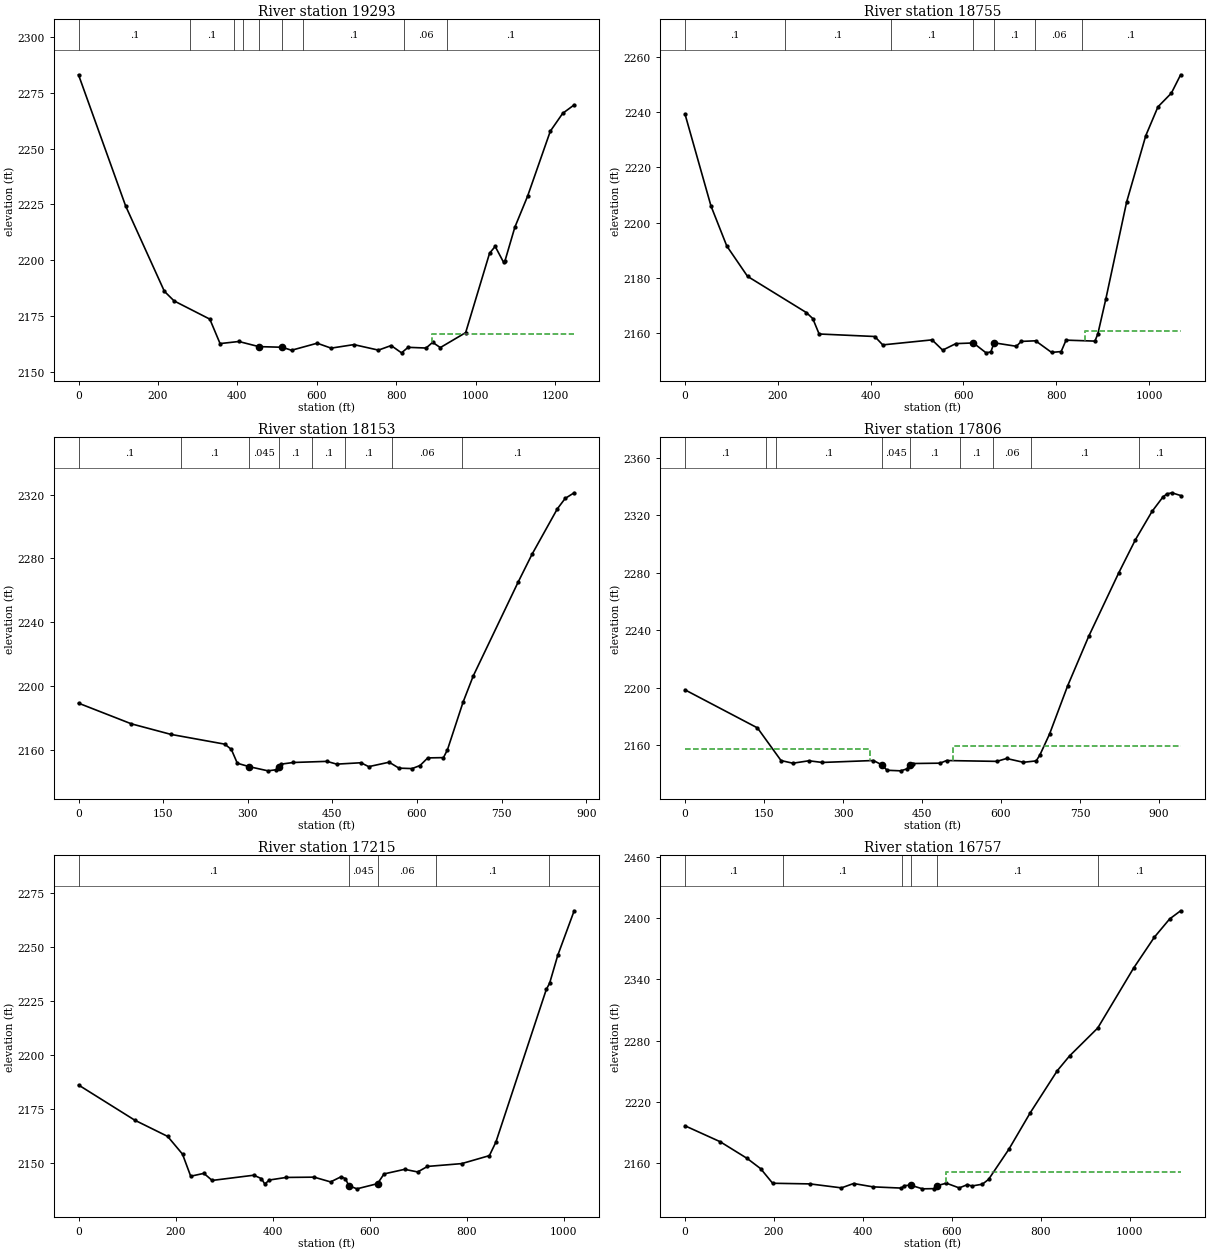
Type RM Length L Ch R = 1 ,19293   ,548.5,537.7,544.4
XS GIS Cut Line= 3
2222317.37811056368245.2721022222221631.96117431368498.397252142
 2221152.7948098368693.188857317
#Sta/Elev= 30
       0 2283.18   118.6 2224.34   216.2 2186.02   240.7 2181.71   330.6 2173.54
   356.4 2162.57   403.7 2163.51     454 2161.21  512.842160.928   536.3 2159.58
   600.9 2162.74   635.9 2160.53   693.3 2162.11   755.1 2159.64   787.1 2161.69
   813.2 2158.42   829.8 2160.89   875.1 2160.58   891.6 2163.13   910.9 2160.78
   974.7 2167.48  1034.9 2203.11    1049 2206.17  1070.3 2199.01  1073.8 2199.74
  1098.6 2214.81  1130.5 2228.64  1187.8 2257.86    1219 2265.87  1247.9 2269.67
#Mann= 9 ,-1 , 0
       0      .1       0  281.48      .1       0  392.13      .1       0
  413.55      .1       0     454    .045       0  512.84      .1       0
  564.33      .1       0  819.98     .06       0  927.56      .1       0
#XS Ineff= 2 , 0
                          889.76         2166.73
Permanent Ineff=
       F       F
Bank Sta=454,512.84
XS Rating Curve= 0 ,0
Exp/Cntr=0.3,0.1

Type RM Length L Ch R = 1 ,18755   ,612.8,602.1,591.3
XS GIS Cut Line= 3
2222063.21129605 367893.188816892221418.41960664368087.980422065
2221042.37803589368207.772177234
#Sta/Elev= 30
       0 2239.37      56 2206.06    90.1 2191.54   134.8 2180.55   261.7 2167.41
   275.4 2165.25   289.1 2159.66     409 2158.75   426.2 2155.71   532.5 2157.53
   555.3 2153.81   583.8 2156.17   621.5 2156.41   648.9 2152.83   659.2 2153.18
   666.1 2156.47   714.2  2155.2   724.6 2156.97   755.6 2157.19     790 2152.99
   810.7 2153.29   821.3 2157.43   883.5 2157.08   889.8  2159.7   907.1 2172.42
   951.8 2207.47   993.1 2231.53  1019.3 2241.96  1048.2 2246.92  1068.2 2253.58
#Mann= 7 ,-1 , 0
       0      .1       0  215.37      .1       0  443.87      .1       0
   621.5    .045       0   666.1      .1       0  754.79     .06       0
  855.21      .1       0
#XS Ineff= 2 , 0
                           861.8         2160.65
Permanent Ineff=
       F       F
Bank Sta=621.5,666.1
XS Rating Curve= 0 ,0
Exp/Cntr=0.3,0.1

Type RM Length L Ch R = 1 ,18153   ,339,346.5,352
XS GIS Cut Line= 3
2221535.08636805367344.2305972282221236.12797648367617.147046149
 2220892.3780078367943.188716888
#Sta/Elev= 30
       0 2189.15    93.8 2176.16     164 2169.53   259.3 2163.41   270.9 2160.13
   281.5 2151.43     303 2149.24   335.9 2146.66   349.8 2147.32   354.5 2149.11
   359.1 2150.86   380.9 2151.91   440.4 2152.61   457.6 2150.87   500.7 2151.74
   514.4 2149.29   550.6 2152.08     568 2148.36   591.3 2148.07   605.4 2150.01
   619.1 2154.78   646.9 2154.96   653.9  2159.8   681.7 2189.83   699.8 2206.31
   779.2  2265.1   803.8 2282.56   848.8 2311.19   862.7 2317.72   878.6 2321.25
#Mann= 8 ,-1 , 0
       0      .1       0  181.72      .1       0     303    .045       0
   354.5      .1       0  414.16      .1       0  473.17      .1       0
  555.53     .06       0  680.06      .1       0
Bank Sta=303,354.5
XS Rating Curve= 0 ,0
Exp/Cntr=0.3,0.1

Type RM Length L Ch R = 1 ,17806   ,585.8,591,599.9
XS GIS Cut Line= 3
2221435.08623996367101.5220931472220995.50312963367339.022274315
2220604.87792663367544.230525315
#Sta/Elev= 30
       0 2198.48   137.6 2172.01   182.3 2149.32   204.7 2147.46   235.2 2149.15
   260.6 2147.99   357.6 2149.34   373.2 2146.44   383.7 2142.56   409.5 2142.16
     421  2143.5     427 2146.18   432.2 2147.25   484.4 2147.49   496.6 2149.32
   591.9 2148.74   610.5 2150.75   642.4  2148.1   666.7 2149.07   673.5 2153.02
     692 2167.68   726.4 2201.24   766.3  2235.6   823.1 2279.57   855.1 2302.86
   886.6 2322.51   907.2  2332.5   914.5 2334.63   924.2 2335.48   940.9 2333.57
#Mann= 9 ,-1 , 0
       0      .1       0  153.41      .1       0  172.47      .1       0
   373.2    .045       0     427      .1       0  522.64      .1       0
  584.83     .06       0  657.25      .1       0  861.62      .1       0
#XS Ineff= 2 , 0
          352.01 2157.16  509.34         2159.67
Permanent Ineff=
       F       F
Bank Sta=373.2,427
XS Rating Curve= 0 ,0
Exp/Cntr=0.3,0.1

Type RM Length L Ch R = 1 ,17215   ,456.1,458.6,457.2
XS GIS Cut Line= 3
2221350.71140872366631.7303818172220695.50307347366804.647358805
2220359.04475689366877.563879639
#Sta/Elev= 30
       0 2185.98     116 2169.68   183.8 2162.17   214.4 2153.96   231.3 2143.73
   258.5 2145.06   275.5 2141.78   361.4  2144.2   377.2 2142.61     384 2140.12
   393.6 2141.98   428.1 2143.17   485.8  2143.3   519.7  2141.1   541.3 2143.48
   550.3 2142.63   557.1 2139.39     574 2137.89   616.5 2140.29   629.9  2144.8
   672.4 2146.92   699.3 2145.71   719.5 2148.27     790 2149.57   847.1 2153.27
   860.5 2159.52   964.5 2230.25   971.3  2233.1     988 2245.97  1021.9 2266.64
#Mann= 5 ,-1 , 0
       0      .1       0   557.1    .045       0   616.5     .06       0
  736.73      .1       0  969.76      .1       0
Bank Sta=557.1,616.5
XS Rating Curve= 0 ,0
Exp/Cntr=0.3,0.1

Type RM Length L Ch R = 1 ,16757   ,571.1,566.4,563.9
XS GIS Cut Line= 2
2221131.96119006366241.1055068972220046.54472572366496.313985974
#Sta/Elev= 30
       0 2196.71    79.2  2181.1   139.9 2164.74   170.2 2154.72   197.2 2140.43
   281.4  2139.8     352 2135.92   379.3 2140.19   422.9 2136.91     487  2135.7
   493.7 2138.11   507.5 2138.58   534.2 2134.97   559.4 2135.15   567.9 2138.18
   588.1  2140.5   616.9 2135.87   635.3 2139.09   645.4 2137.75     669 2139.51
     683 2144.24   728.6 2173.72   776.8 2209.53   837.5 2250.63     865 2265.05
   928.5 2292.44    1009 2350.98    1056 2381.43  1090.3 2399.25    1115 2407.24
#Mann= 6 ,-1 , 0
       0      .1       0  219.57      .1       0  489.15     .06       0
   507.5    .045       0   567.9      .1       0  929.66      .1       0
#XS Ineff= 2 , 0
                          586.76         2151.44
Permanent Ineff=
       F       F
Bank Sta=507.5,567.9
XS Rating Curve= 0 ,0
Exp/Cntr=0.3,0.1

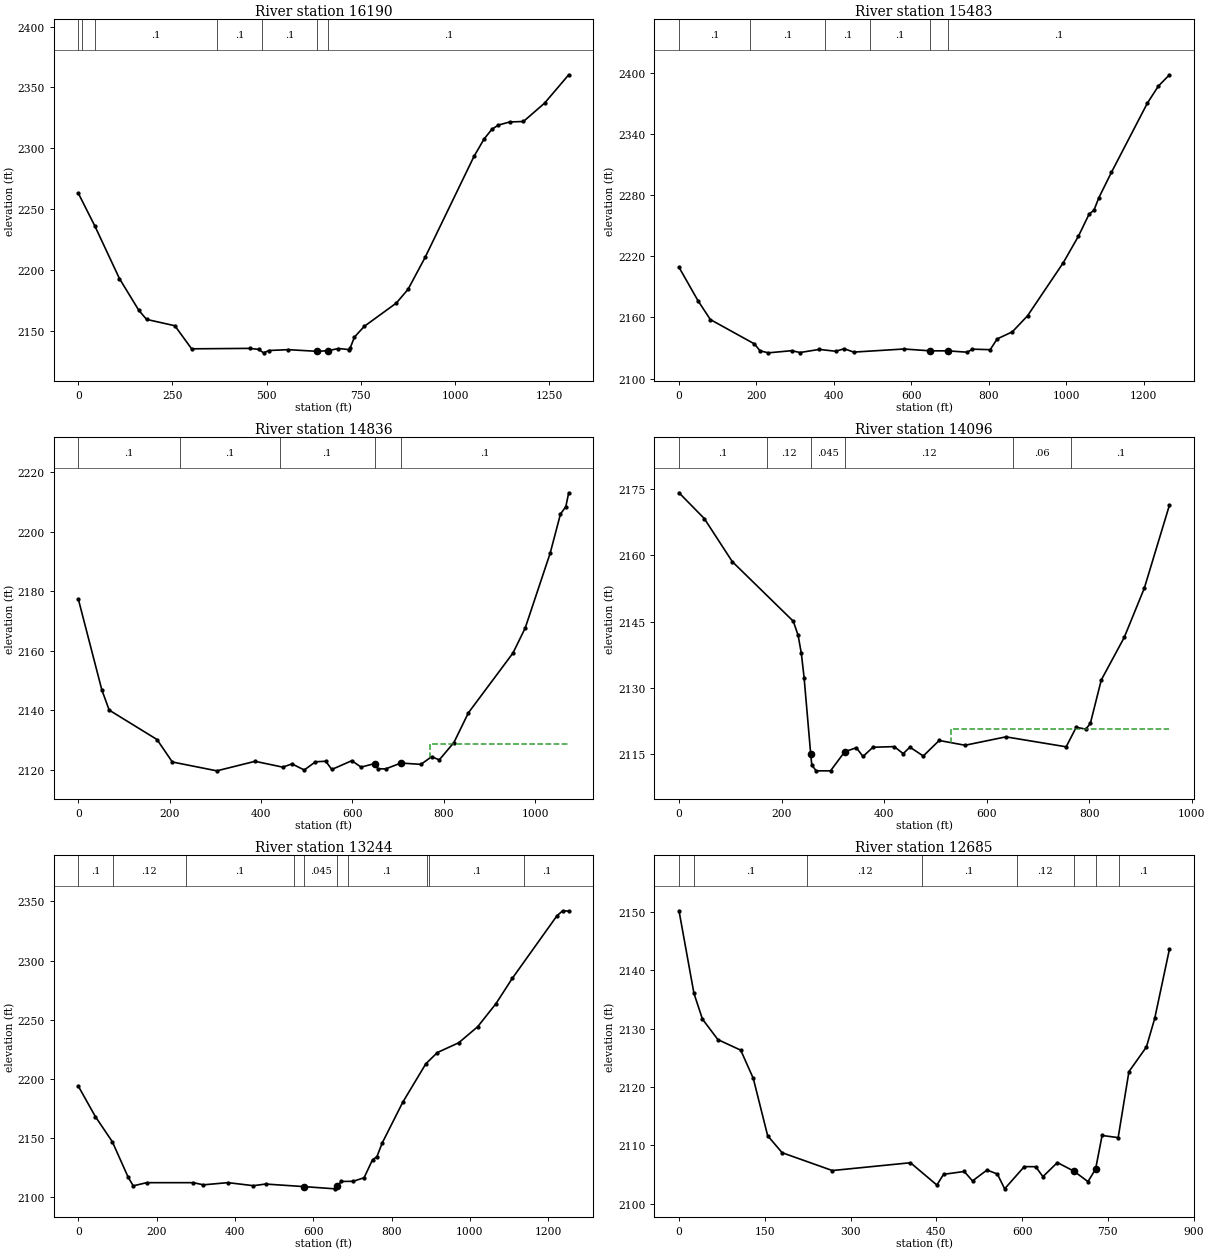
Type RM Length L Ch R = 1 ,16190   ,705.1,707.5,704.2
XS GIS Cut Line= 2
2221015.54606855365658.4491918982219766.25919706366023.873985976
#Sta/Elev= 30
       0 2263.12    44.5 2235.81   109.4 2192.85   160.7 2166.84   181.2 2159.37
   256.4 2154.14   300.9 2135.18   454.7 2135.54   478.6 2134.73   491.9 2131.88
     506  2133.8   557.2 2134.49  633.89 2133.12   663.2 2133.65   690.5 2135.44
   717.9 2134.59   721.3 2135.53   732.9 2144.79   758.9  2153.6     844 2172.76
   875.1 2184.02   920.7 2210.43  1050.2  2293.3  1076.8 2307.51  1097.3 2315.45
  1114.4 2318.99  1145.2 2321.61  1181.4 2321.98  1237.5 2337.05  1301.6 2360.37
#Mann= 7 ,-1 , 0
       0      .1       0   10.06      .1       0   44.56      .1       0
  368.59      .1       0  487.11      .1       0  633.89    .045       0
   663.2      .1       0
Bank Sta=633.89,663.2
XS Rating Curve= 0 ,0
Exp/Cntr=0.3,0.1

Type RM Length L Ch R = 1 ,15483   ,643.5,647.2,656.2
XS GIS Cut Line= 2
2220647.22790755364981.8419493142219480.13181655 365474.78846997
#Sta/Elev= 30
       0 2209.09      49 2176.34      81 2157.84     195 2133.95   209.2 2127.24
   230.6 2125.22   291.2 2127.33   312.5 2125.53   362.4 2128.58   405.1 2126.75
   426.5 2129.24   451.4 2125.95   581.1 2128.98   648.7 2127.19   693.8 2127.18
   744.8 2125.84   757.7 2128.83   803.9 2128.31   821.8 2138.86     861 2145.81
   900.2 2161.47   992.8 2213.67  1031.8  2239.6  1059.3  2261.2  1071.9    2265
  1084.4 2277.21  1116.9 2302.07    1210  2370.1  1238.5  2386.8  1266.9 2397.78
#Mann= 6 ,-1 , 0
       0      .1       0  184.58      .1       0  375.83      .1       0
  494.01      .1       0   648.7    .045       0   693.8      .1       0
Bank Sta=648.7,693.8
XS Rating Curve= 0 ,0
Exp/Cntr=0.3,0.1

Type RM Length L Ch R = 1 ,14836   ,755.2,739.3,703.1
XS GIS Cut Line= 2
2220330.91489188364621.1753478052219281.96128114364851.522328064
#Sta/Elev= 30
       0 2177.43    51.5 2146.92    67.7 2140.07   172.4 2130.19     206 2122.64
   303.4 2119.67   387.2 2122.87   447.8 2120.91     468    2122   494.9 2119.95
   519.4 2122.71   541.9 2122.89   555.2 2120.13     599 2123.08   619.2 2120.92
   648.9  2122.1   656.1 2120.38   672.9 2120.31   706.5 2122.29   750.2 2121.84
   773.7 2124.41   790.5 2123.36   822.5 2129.17   854.3 2139.17   951.8 2159.22
   978.6 2167.63  1033.4 2192.82  1055.9 2205.94  1067.5 2208.36  1073.9 2213.05
#Mann= 5 ,-1 , 0
       0      .1       0  222.75      .1       0  441.62      .1       0
   648.9    .045       0   706.5      .1       0
#XS Ineff= 2 , 0
                          769.44         2128.64
Permanent Ineff=
       F       F
Bank Sta=648.9,706.5
XS Rating Curve= 0 ,0
Exp/Cntr=0.3,0.1

Type RM Length L Ch R = 1 ,14096   ,812.9,852.4,856.9
XS GIS Cut Line= 3
2219816.33619663363829.6470752212219622.58625606364092.147206396
2219208.00309572364567.147240639
#Sta/Elev= 30
       0 2174.18    49.3 2168.35     104 2158.59   222.9 2145.11   232.3 2141.94
   238.6 2137.85     244 2132.36   256.9 2115.05     259 2112.58   267.5 2111.25
   295.6 2111.25   323.2 2115.57   345.9 2116.48   358.9  2114.5   378.3 2116.59
   419.9 2116.73   437.3 2115.14   450.4 2116.61   476.5 2114.61   507.5 2118.12
     558 2117.04   637.6 2118.94   755.2 2116.69   774.9 2121.13   793.5 2120.67
   802.4    2122   823.7 2131.82   868.4 2141.43   907.6 2152.58   956.7  2171.4
#Mann= 6 ,-1 , 0
       0      .1       0  171.21     .12       0   256.9    .045       0
   323.2     .12       0   650.9     .06       0  765.54      .1       0
#XS Ineff= 2 , 0
                          530.84         2120.64
Permanent Ineff=
       F       F
Bank Sta=256.9,323.2
XS Rating Curve= 0 ,0
Exp/Cntr=0.3,0.1

Type RM Length L Ch R = 1 ,13244   ,564.8,559.4,555.6
XS GIS Cut Line= 3
2219439.25296131363473.3971315622218785.08629064363810.897112727
2218324.66988863364044.230307475
#Sta/Elev= 30
       0 2193.79    43.7 2167.94      87 2146.66   127.6 2116.53   140.4 2109.32
   174.5    2112   293.7 2112.01   319.6 2110.19   382.3 2112.04   447.3 2109.45
   478.3 2110.85   575.5  2108.7   655.5 2106.79   661.6 2108.83   671.3 2113.02
     702 2113.17   729.8 2116.19   751.4 2131.42   762.5 2133.93   776.1  2145.6
   828.7 2180.17   887.5 2212.62   916.9 2222.14   971.4  2230.4  1019.9 2244.01
  1066.6 2263.56  1108.1 2284.85  1222.2 2337.85  1236.9 2342.12  1252.3 2341.82
#Mann= 10 ,-1 , 0
       0      .1       0   88.15     .12       0  274.59      .1       0
  551.09     .12       0   575.5    .045       0   661.6     .06       0
  687.48      .1       0  889.98      .1       0  896.38      .1       0
 1139.32      .1       0
Bank Sta=575.5,661.6
XS Rating Curve= 0 ,0
Exp/Cntr=0.3,0.1

Type RM Length L Ch R = 1 ,12685   ,937.1,946.3,939.9
XS GIS Cut Line= 3
2219180.91948847363034.8556858152218480.36999784363360.949234488
2218403.54436982363397.044468678
#Sta/Elev= 30
       0 2150.24    26.1 2136.08      41 2131.65      68 2128.13   107.9 2126.32
   129.9 2121.47     155 2111.64   180.3 2108.72   268.1 2105.66   404.7    2107
   450.9 2103.17   462.6 2105.01   498.7  2105.5   513.2 2103.88   538.6 2105.75
   556.7 2105.06   569.4 2102.52   603.7 2106.33   623.7 2106.32   636.3 2104.61
   661.6 2107.03   690.62105.548   715.1 2103.76  728.442105.917   739.8 2111.68
   767.9 2111.31   786.7 2122.63   817.3 2126.87   831.8 2131.76   857.6 2143.68
#Mann= 8 ,-1 , 0
       0      .1       0   27.01      .1       0  224.52     .12       0
  424.18      .1       0  590.26     .12       0   690.6    .045       0
  728.44     .06       0  768.61      .1       0
Bank Sta=690.6,728.44
XS Rating Curve= 0 ,0
Exp/Cntr=0.3,0.1