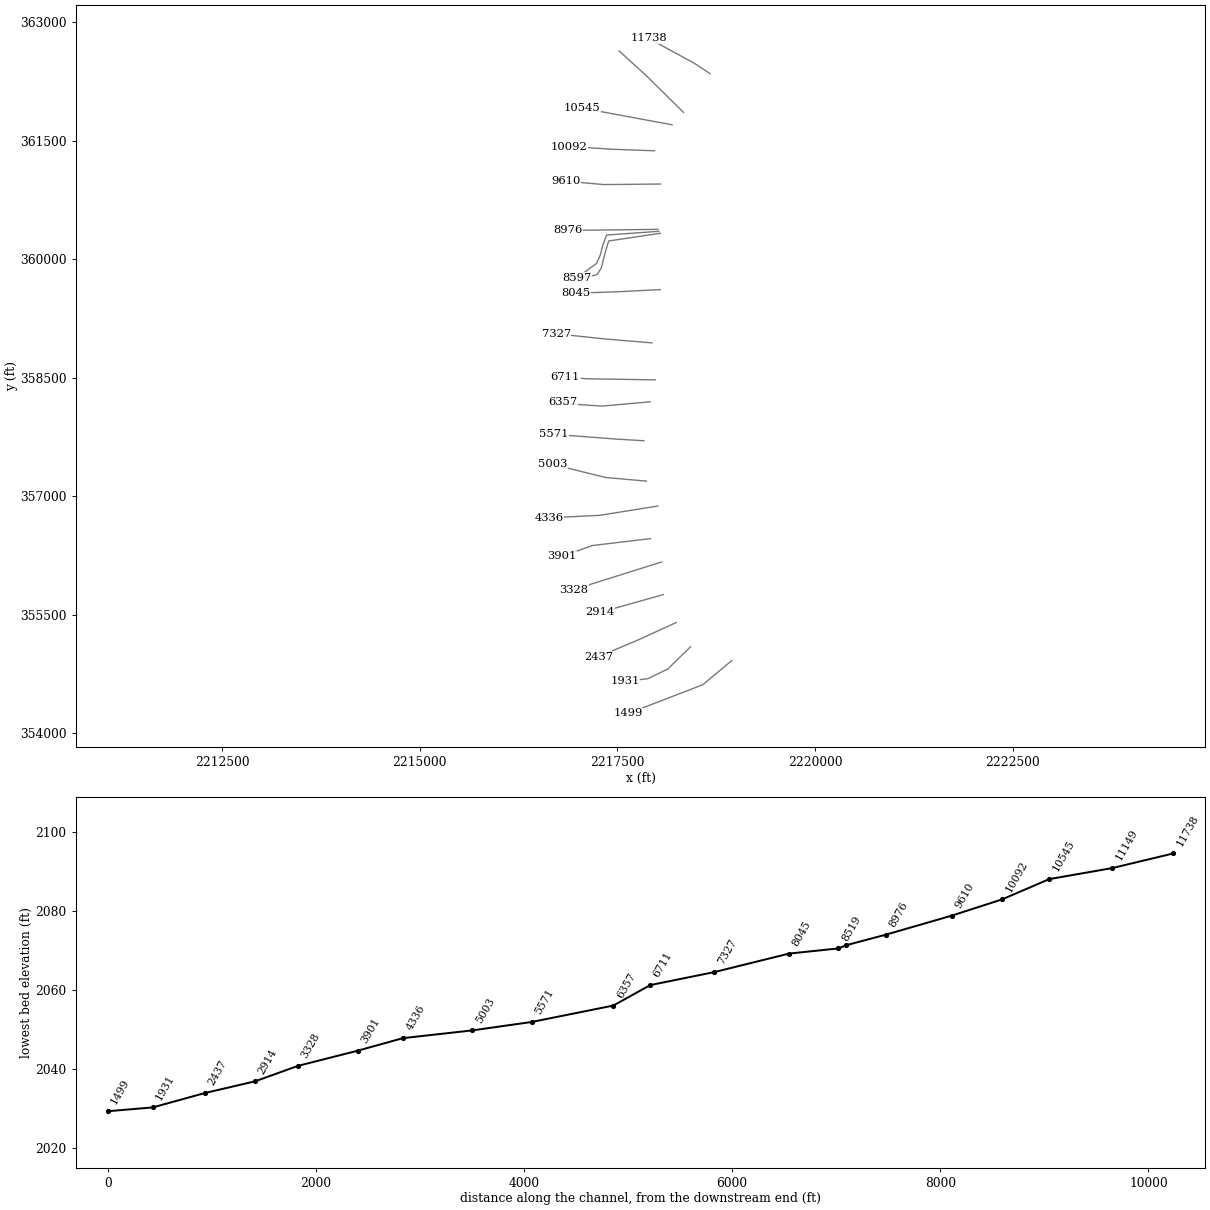
HEC-RAS study NFANTNYCK.prj: NFANTNYCK

--- NFANTNYCK.g01 (geometry) --- (continued)

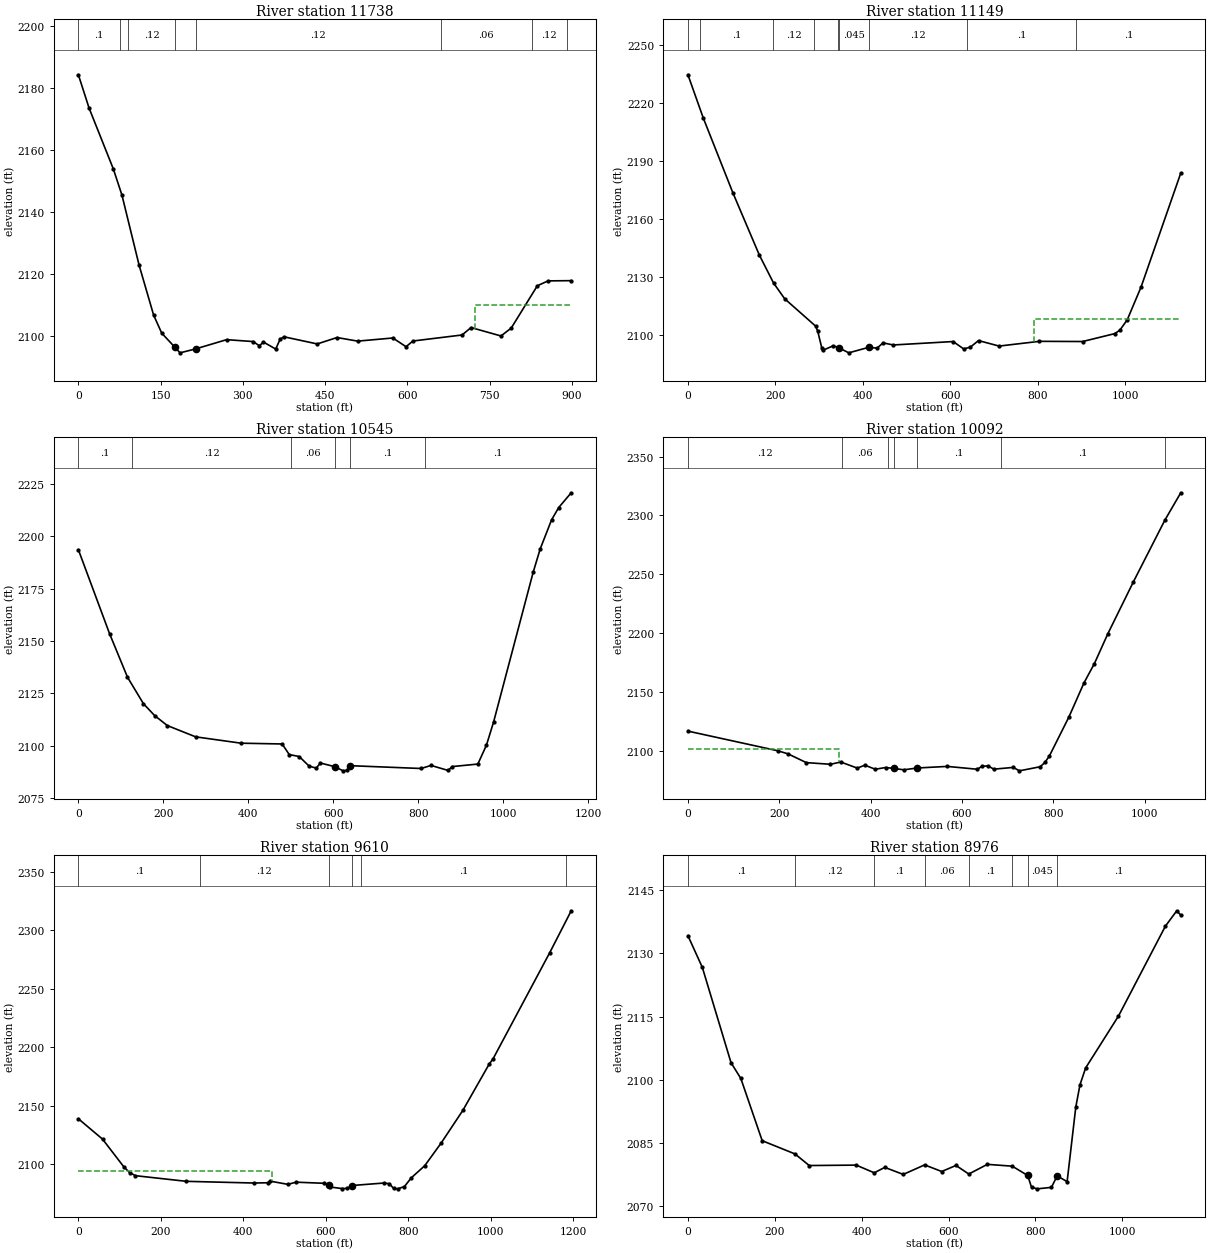
Type RM Length L Ch R = 1 ,11738   ,590.7,589.4,589.5
XS GIS Cut Line= 3
2218673.62785214362351.5220787232218473.62792405362483.466696724
2217894.46143147362798.744281396
#Sta/Elev= 30
       0 2184.31    19.5 2173.58    63.7 2153.96    79.4 2145.54   110.8 2122.86
   137.3 2106.75   152.1 2100.93   175.8 2096.44   185.5 2094.59  213.822095.859
   270.4 2098.84   318.9 2098.23   330.1 2096.87   337.6 2098.06     360 2095.81
     368    2099     375 2099.77   435.7 2097.46   471.8 2099.53   509.4 2098.37
   573.6 2099.38   597.7 2096.57   610.3 2098.41   699.9 2100.35   716.3 2102.75
   770.9 2100.03   789.6 2102.59   837.2 2116.23   856.8 2117.81     899 2117.88
#Mann= 8 ,-1 , 0
       0      .1       0   75.89      .1       0   91.14     .12       0
   175.8    .045       0  213.82     .12       0  660.63     .06       0
  826.97     .12       0   891.3     .06       0
#XS Ineff= 2 , 0
                          722.69         2110.15
Permanent Ineff=
       F       F
Bank Sta=175.8,213.82
XS Rating Curve= 0 ,0
Exp/Cntr=0.3,0.1

Type RM Length L Ch R = 1 ,11149   ,594.3,603.9,604.8
XS GIS Cut Line= 3
2218337.76326161361861.0609821232217867.67214744362324.724668362
2217522.99369408362639.193012125
#Sta/Elev= 30
       0 2234.64    35.2 2212.22   102.9 2173.55   163.2 2141.47   195.7    2127
   221.2 2118.83   292.2 2104.64   296.9 2101.96   306.2 2093.29   309.4 2092.28
   332.6 2094.55   344.2 2093.57   344.8  2093.5   367.8 2090.87   413.9 2093.75
   432.4 2093.28   446.2 2096.02   469.5 2094.94   606.4 2096.71   630.5  2092.9
   645.8 2093.82   664.4 2097.21   711.5 2094.37   803.7 2096.82   902.5 2096.72
   975.6 2100.79   987.5 2102.54  1004.6    2108  1036.2 2124.96  1126.9 2183.82
#Mann= 9 ,-1 , 0
       0      .1       0   28.49      .1       0  194.67     .12       0
  289.03      .1       0   344.2    .045       0   344.8    .045       0
   413.9     .12       0  637.57      .1       0  888.37      .1       0
#XS Ineff= 2 , 0
                          790.49         2108.34
Permanent Ineff=
       F       F
Bank Sta=344.8,413.9
XS Rating Curve= 0 ,0
Exp/Cntr=0.3,0.1

Type RM Length L Ch R = 1 ,10545   ,450.3,452.9,455.9
XS GIS Cut Line= 2
2218193.07238281361704.2999479772217052.79480772361915.411074311
#Sta/Elev= 30
       0 2193.61    73.3 2153.59   115.6 2132.76   153.1 2120.14   179.3 2114.49
   209.3  2109.7     276 2104.31     383 2101.28   479.5 2100.91   496.2 2095.86
   519.6 2094.92   542.9 2090.36   559.6 2089.39   569.6 2091.82     603  2090.1
     623 2088.09     633 2088.31   639.7 2090.55   806.5 2089.21   829.9 2090.67
   869.9 2088.28   879.9 2090.13     940 2091.32   960.2 2100.32   977.1 2111.44
  1070.3 2182.94  1086.8 2194.04  1113.5 2207.86  1130.2 2213.72  1159.7 2220.78
#Mann= 6 ,-1 , 0
       0      .1       0  125.19     .12       0  501.49     .06       0
     603    .045       0   639.7      .1       0  815.24      .1       0
Bank Sta=603,639.7
XS Rating Curve= 0 ,0
Exp/Cntr=0.3,0.1

Type RM Length L Ch R = 1 ,10092   ,473.4,482.6,479.7
XS GIS Cut Line= 3
2217970.85005823361375.1332834812217436.12803055361394.577798396
2216893.07235813361429.299841806
#Sta/Elev= 30
       0 2116.71   196.9    2100   219.2 2097.38   259.3 2089.94   311.9 2088.54
   334.8 2090.44   370.9 2085.27   387.4 2087.76   410.3 2084.32   432.9 2085.79
   450.9 2085.01   472.7 2083.84   502.3 2085.39     568 2086.72   633.7 2084.31
   643.6 2086.74   656.7 2087.21   669.9 2084.39   712.6 2085.87   725.8 2082.96
   771.4 2086.44   781.7  2090.1   791.5 2095.59   834.3 2128.75   867.1 2157.56
   890.1 2174.13   919.7 2199.59   975.6 2243.67  1044.7  2296.2  1079.2 2319.21
#Mann= 7 ,-1 , 0
       0     .12       0  337.33     .06       0  437.44      .1       0
   450.9    .045       0   502.3      .1       0  686.14      .1       0
 1045.29      .1       0
#XS Ineff= 2 , 0
          330.73 2101.26
Permanent Ineff=
       F       F
Bank Sta=450.9,502.3
XS Rating Curve= 0 ,0
Exp/Cntr=0.3,0.1

Type RM Length L Ch R = 1 ,9610    ,635.3,633.7,640.5
XS GIS Cut Line= 3
 2218045.8502363360954.3001356422217326.40580906360947.355595723
2216852.79455155360990.410955817
#Sta/Elev= 30
       0 2138.81    58.6 2121.39   110.2 2097.69   124.2  2092.8   138.4 2090.12
     262 2085.28     426 2083.83   458.8 2084.06   465.4 2085.42   508.1 2082.69
   527.7 2084.56   596.6  2083.6   606.5 2081.73   609.8 2080.46   638.7 2079.13
   652.4 2079.17   662.3 2081.68   741.1 2083.84   754.3 2083.21   764.2 2079.22
     774 2078.86   790.5 2080.78     807 2088.19   839.9 2098.68   879.5 2117.98
   932.2 2145.98   996.1 2185.61  1005.2 2189.92    1143    2281    1195  2316.8
#Mann= 6 ,-1 , 0
       0      .1       0  295.67     .12       0   606.5    .045       0
   662.3     .12       0  684.73      .1       0 1183.01    .055       0
#XS Ineff= 2 , 0
          469.27 2093.72
Permanent Ineff=
       F       F
Bank Sta=606.5,662.3
XS Rating Curve= 0 ,0
Exp/Cntr=0.3,0.1

Type RM Length L Ch R = 1 ,8976    ,340.7,378.7,417.8
XS GIS Cut Line= 2
2218013.90574639360380.6887500582216879.18360639360366.799998313
#Sta/Elev= 30
       0 2134.22    33.2 2126.67    99.2 2104.03   121.8 2100.28     171 2085.48
   246.5 2082.34   279.3 2079.58   387.5 2079.68     429 2077.85   453.2 2079.14
   495.8 2077.47     545 2079.73   584.4 2078.16   617.2  2079.6   646.7 2077.56
   689.4 2079.86   746.7 2079.43   782.3 2077.22   791.1 2074.42   804.2 2074.04
     837 2074.39   850.2 2077.13   873.1 2075.75   893.1  2093.5   902.7 2098.77
   915.8 2102.79   991.3  2115.1  1099.5  2136.5  1125.6 2140.14  1134.8  2139.1
#Mann= 8 ,-1 , 0
       0      .1       0   246.5     .12       0     429      .1       0
     545     .06       0   646.7      .1       0   746.7      .1       0
   782.3    .045       0   850.2      .1       0
Bank Sta=782.3,850.2
XS Rating Curve= 0 ,0
Exp/Cntr=0.5,0.3

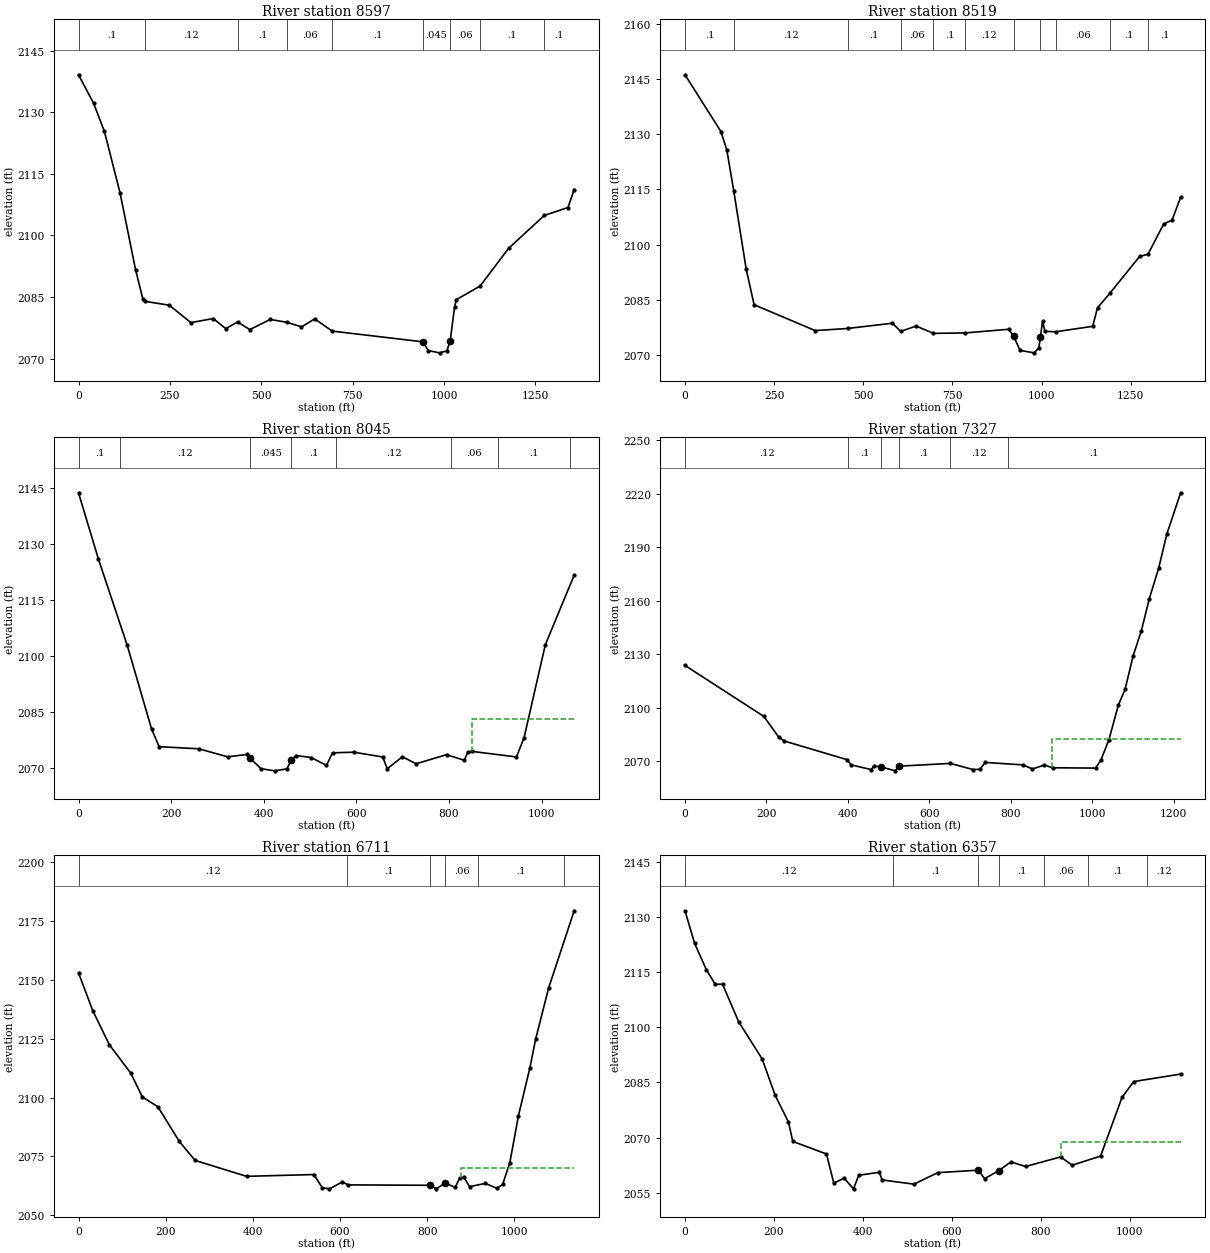
Type RM Length L Ch R = 1 ,8597    ,73.4,77.7,83
XS GIS Cut Line= 6
2218025.01694463360355.6888000672217363.90573405360308.466781646
2217311.12795247360162.6334118992217287.51677921360064.022060558
2217238.90565597359950.133180723 2216986.1279463359765.411109224
#Sta/Elev= 30
       0 2139.18    41.1 2132.26    70.7 2125.41   113.5 2110.45   156.2 2091.61
     176 2084.56   182.5 2083.93   248.3 2083.01   307.4 2078.76   368.8 2079.75
   402.9 2077.29   435.3 2078.91   468.7 2077.06   524.6 2079.53   570.7 2078.83
   610.1 2077.72   646.3 2079.67   694.1 2076.69   941.9 2074.08   957.5 2071.93
   987.9 2071.39  1007.9 2071.87  1017.1 2074.36  1028.9 2082.51  1033.9 2084.37
  1098.8 2087.67  1176.7 2096.85  1274.3 2104.88  1339.3 2106.82  1356.2 2111.19
#Mann= 9 ,-1 , 0
       0      .1       0   182.5     .12       0   435.3      .1       0
   570.7     .06       0   694.1      .1       0   941.9    .045       0
  1017.1     .06       0  1098.8      .1       0  1274.3      .1       0
#XS Ineff= 2 , 0
             916  2073.6    1042          2073.6
Permanent Ineff=
       F       F
Bank Sta=941.9,1017.1
XS Rating Curve= 0 ,0
Exp/Cntr=0.5,0.3

Type RM Length L Ch R = 1 ,8519    ,530.3,474.6,430.4
XS GIS Cut Line= 6
2218044.46145955 360330.688850062217390.29478888360233.466603562
2217347.23910072360089.0223386442217297.23920073359890.411187306
2217244.46141914359808.4667973972216976.40585288359744.577817559
#Sta/Elev= 30
       0 2146.15   100.9 2130.71   117.5 2125.61     137 2114.45   171.6 2093.34
   193.8 2083.64   365.1 2076.61   455.8 2077.18   581.9 2078.62   604.8 2076.38
   648.2 2077.85   696.7 2075.85   785.8 2075.97     908 2076.97   921.5 2075.08
   939.7 2071.22     979 2070.56   992.5 2071.93   996.5 2074.83  1002.7 2079.12
  1009.5 2076.41  1039.4 2076.29  1143.3 2077.77  1156.8 2082.81    1193 2086.94
  1274.9 2096.77  1298.5 2097.38  1342.3 2105.59  1365.9 2106.64  1389.9 2112.86
#Mann= 11 ,-1 , 0
       0      .1       0     137     .12       0   455.8      .1       0
   604.8     .06       0   696.7      .1       0   785.8     .12       0
   921.5    .045       0   996.5      .1       0  1039.4     .06       0
    1193      .1       0  1298.5      .1       0
Bank Sta=921.5,996.5
XS Rating Curve= 0 ,0
Exp/Cntr=0.5,0.3

Type RM Length L Ch R = 1 ,8045    ,727.7,718,706.9
XS GIS Cut Line= 3
2218043.07235472359618.1889627282217538.90571214359591.799907893
2216973.62797131359572.355392978
#Sta/Elev= 30
       0 2143.76    42.7 2126.12   105.1 2102.92   157.7  2080.5   174.1 2075.72
   259.6 2075.16     322 2073.01   364.7 2073.65   371.3 2072.56   394.2 2069.82
   423.8 2069.25   450.1 2069.78     460 2072.23   469.8 2073.35   502.1 2072.82
   535.5 2070.73   548.6 2074.08   594.6 2074.25     657 2072.96   666.8 2069.81
   699.6 2073.02   729.2 2071.14   794.8 2073.58   833.1 2072.08   840.8 2074.29
   850.6 2074.45   945.8 2072.97   962.3 2078.12  1008.2 2103.04  1070.5 2121.68
#Mann= 8 ,-1 , 0
       0      .1       0   90.16     .12       0   371.3    .045       0
     460      .1       0  556.88     .12       0  803.79     .06       0
  905.04      .1       0 1061.92      .1       0
#XS Ineff= 2 , 0
                           848.9         2083.18
Permanent Ineff=
       F       F
Bank Sta=371.3,460
XS Rating Curve= 0 ,0
Exp/Cntr=0.3,0.1

Type RM Length L Ch R = 1 ,7327    ,618.8,615.7,617.1
XS GIS Cut Line= 3
2217937.51679155358943.1890003982217341.68366563358993.188900396
2216726.40569672359058.466656983
#Sta/Elev= 30
       0 2123.64   193.6 2095.08   229.7  2083.6   243.1 2081.33   397.8 2070.84
   407.7 2067.91   457.1 2065.28   463.9 2067.27   480.1 2066.83   516.3 2064.57
   524.7 2067.19   651.4 2068.73   707.5 2065.27     724 2065.44   737.2 2069.27
   829.6 2067.92   852.7 2065.64   882.4 2067.82   902.2 2066.29  1007.8 2066.11
    1021 2070.58  1040.8  2082.1  1063.8  2101.4  1080.3 2110.22  1100.1 2129.04
  1120.4 2143.17  1139.7 2160.98  1162.8 2178.16  1182.6 2197.13  1216.7 2220.41
#Mann= 6 ,-1 , 0
       0     .12       0  400.78      .1       0   480.1    .045       0
   524.7      .1       0  649.79     .12       0  792.66      .1       0
#XS Ineff= 2 , 0
                          900.85         2082.39
Permanent Ineff=
       F       F
Bank Sta=480.1,524.7
XS Rating Curve= 0 ,0
Exp/Cntr=0.3,0.1

Type RM Length L Ch R = 1 ,6711    ,355.1,353.8,349.1
XS GIS Cut Line= 3
2217979.18370298358475.1331779812217101.40560289358489.022257805
2216843.07245813358515.410984561
#Sta/Elev= 30
       0 2152.86    32.6 2136.87    70.6 2122.43   119.9 2110.34   146.5 2100.24
   182.2 2096.08   231.4 2081.36   267.5 2073.34   385.6 2066.58     540 2067.34
   559.6 2061.75     576 2061.28   605.5 2064.21   618.6 2062.96  807.812062.779
   820.8 2061.28   841.7 2063.73   864.7 2061.87   874.5 2065.83   884.4 2066.21
   897.6  2062.2   933.9 2063.58   960.3  2061.5   973.5 2063.16     990 2072.43
  1009.7 2092.27  1036.1  2112.7  1049.3 2124.85    1079 2146.44  1137.6 2179.17
#Mann= 6 ,-1 , 0
       0     .12       0  616.54      .1       0  807.81    .045       0
   841.7     .06       0  915.96      .1       0 1114.96      .1       0
#XS Ineff= 2 , 0
                           878.1          2070.1
Permanent Ineff=
       F       F
Bank Sta=807.81,841.7
XS Rating Curve= 0 ,0
Exp/Cntr=0.3,0.1

Type RM Length L Ch R = 1 ,6357    ,780.5,786,781.9
XS GIS Cut Line= 4
2217913.90561831358197.3555183112217309.73917572358143.188959971
2216854.18365639358172.3555683052216805.57253313358190.410978392
#Sta/Elev= 30
       0 2131.65    21.8 2122.77    48.2 2115.61      68 2111.67    84.4 2111.72
   120.7 2101.51   173.4 2091.44     203 2081.49   232.7 2074.27   242.5 2068.99
   318.3 2065.57   334.8 2057.64   357.9 2059.02   379.1 2056.11   390.8  2059.8
   436.9  2060.6   443.5 2058.52   515.1 2057.38   568.7 2060.51   659.8 2061.18
   673.9 2058.86   706.2 2061.08   733.1 2063.43     766 2062.18   844.9 2064.78
   871.2 2062.54   934.8 2065.01     983 2080.94  1009.3 2085.25  1114.9 2087.29
#Mann= 7 ,-1 , 0
       0     .12       0  469.02      .1       0   659.8    .045       0
   706.2      .1       0  807.23     .06       0  907.03      .1       0
 1038.65     .12       0
#XS Ineff= 2 , 0
                          844.82         2068.77
Permanent Ineff=
       F       F
Bank Sta=659.8,706.2
XS Rating Curve= 0 ,0
Exp/Cntr=0.3,0.1

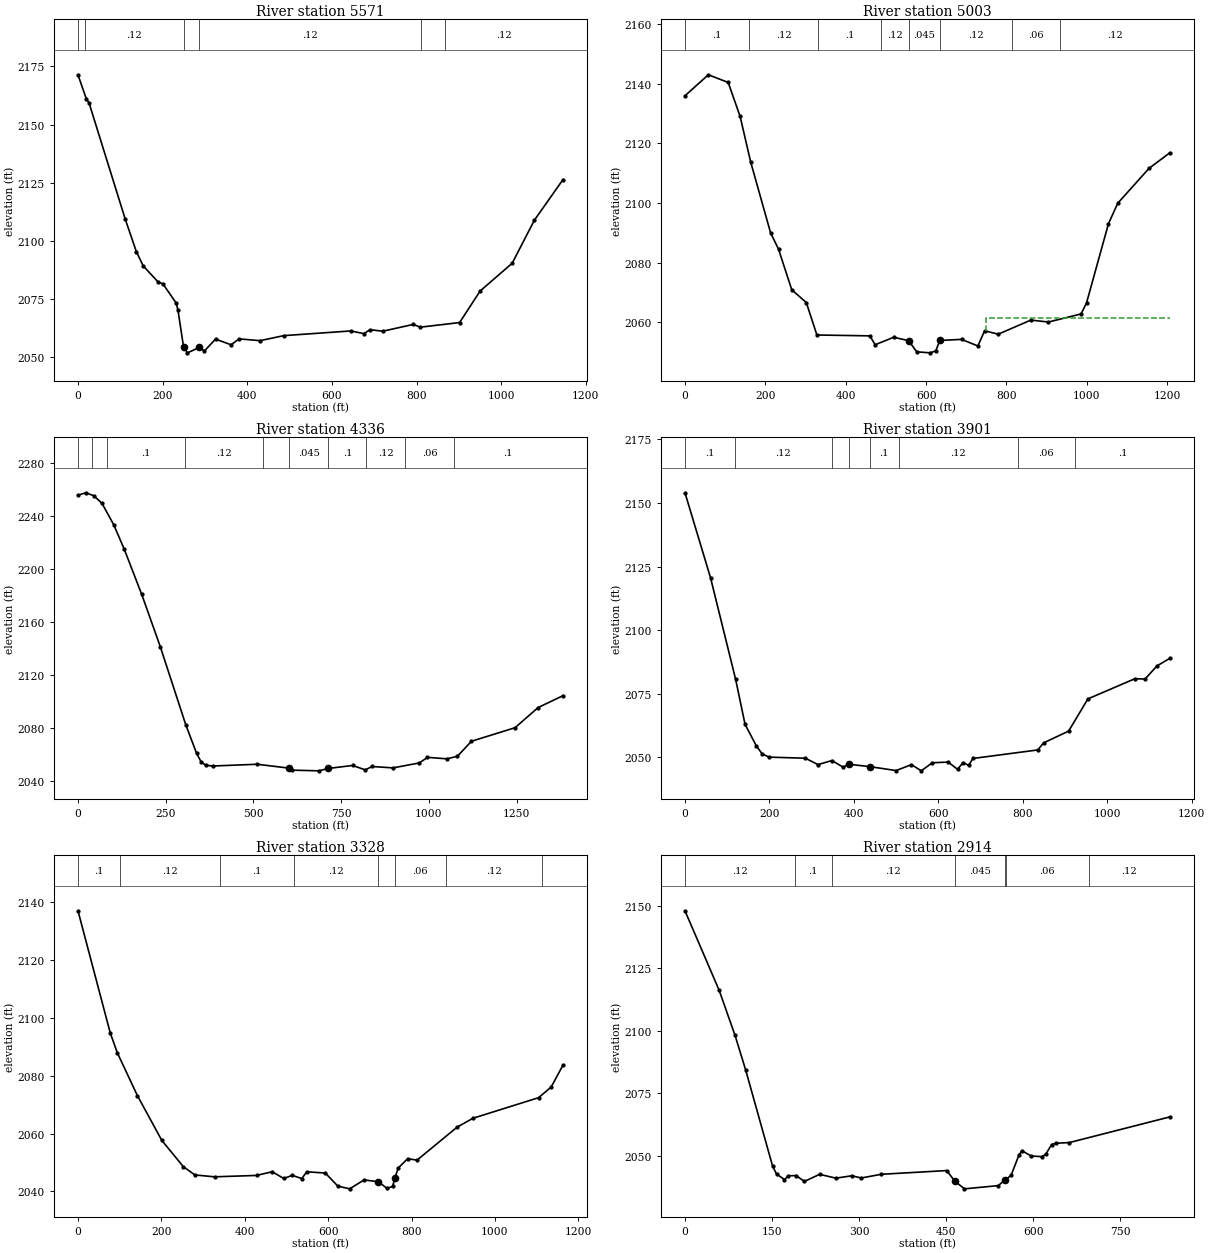
Type RM Length L Ch R = 1 ,5571    ,557.4,567.9,565
XS GIS Cut Line= 3
2217836.12788673357704.3000739812217487.51703538357725.133365646
2216693.07243006357786.244463891
#Sta/Elev= 30
       0 2171.39    19.5 2161.14    26.1 2159.33   111.5 2109.47   137.8 2095.48
   154.2 2089.28   190.2 2082.23   200.6 2081.62   232.1 2073.34   236.4 2070.16
   249.5 2054.47   258.8 2051.95   286.7 2054.26   298.8 2052.76   325.1 2057.85
   361.7 2055.42   381.1 2057.94   430.4 2057.18   486.3 2059.34   644.3 2061.35
   675.4 2060.21   690.4 2061.89     720 2061.23   792.4 2064.16   808.8 2062.97
   901.8 2064.96   950.3  2078.5    1026 2090.42  1078.6 2108.95    1146 2126.35
#Mann= 6 ,-1 , 0
       0      .1       0   16.25     .12       0   249.5    .045       0
   286.7     .12       0  810.36     .06       0  866.48     .12       0
Bank Sta=249.5,286.7
XS Rating Curve= 0 ,0
Exp/Cntr=0.3,0.1

Type RM Length L Ch R = 1 ,5003    ,660.7,667.8,660.9
XS GIS Cut Line= 4
2217868.07237664 357193.188891472217354.18364064357239.022133142
2217216.68358755357272.3553998172216683.35033664357404.300017804
#Sta/Elev= 30
       0 2135.98    58.2 2143.02   107.6 2140.44   137.2 2129.06   163.6 2113.74
     213 2090.06   232.8 2084.56   265.7 2070.97   301.9 2066.69   328.3 2055.81
     460 2055.52   473.2 2052.55   519.4 2055.05   556.5 2053.91   576.7 2050.16
   610.6 2049.83   624.1  2050.5   634.2 2053.98   688.2 2054.34   728.8 2052.13
   745.7 2057.22   779.5 2056.08   860.6  2060.8   904.5 2060.16   985.6 2062.86
   999.2 2066.54  1053.8 2093.09  1076.9 2099.96  1154.6 2111.63  1206.8 2116.91
#Mann= 8 ,-1 , 0
       0      .1       0  158.89     .12       0     332      .1       0
  488.58     .12       0   556.5    .045       0   634.2     .12       0
  814.61     .06       0  933.04     .12       0
#XS Ineff= 2 , 0
                          747.93         2061.41
Permanent Ineff=
       F       F
Bank Sta=556.5,634.2
XS Rating Curve= 0 ,0
Exp/Cntr=0.3,0.1

Type RM Length L Ch R = 1 ,4336    ,410.6,434.5,439.2
XS GIS Cut Line= 3
2218012.51696964356877.9109787342217273.62802747356759.855440557
2216640.29464847356729.300055474
#Sta/Elev= 30
       0 2255.85    22.2  2257.7    45.5 2255.41    68.7 2249.62     102 2233.52
   131.9  2215.1   181.7 2181.02   234.9 2141.34   307.3 2082.59   337.9 2061.19
   351.1 2054.59   364.4 2052.07   384.4 2051.51   510.7 2052.84   602.4 2049.89
   610.3  2048.4   686.7 2047.87   713.3 2049.67     783 2051.93   818.8 2048.59
   838.5 2051.15   897.6 2050.09   973.2 2053.84   996.2 2058.06    1052 2056.92
  1081.6 2058.88  1121.4 2070.17  1245.8 2080.43  1311.5 2095.62  1382.3 2104.56
#Mann= 10 ,-1 , 0
       0      .1       0   39.31     .12       0   81.43      .1       0
  305.65     .12       0  528.66      .1       0   602.4    .045       0
   713.3      .1       0  822.36     .12       0  932.64     .06       0
 1070.61      .1       0
Bank Sta=602.4,713.3
XS Rating Curve= 0 ,0
Exp/Cntr=0.3,0.1

Type RM Length L Ch R = 1 ,3901    ,565,572.9,563.9
XS GIS Cut Line= 3
2217919.46138147356465.4111475652217186.12787439 356377.91099447
2216800.01676998356240.410941392
#Sta/Elev= 30
       0 2154.03    60.6 2120.56     120 2080.63   142.2 2063.01   168.8 2054.57
   182.8 2051.34   199.3 2050.08   285.2 2049.65     315 2047.14     348 2048.74
   374.4 2046.14   387.7 2047.28     437 2046.36     500  2044.8   536.3 2047.14
   559.5 2044.69   585.9 2047.88   623.4 2048.12   645.4 2045.29   658.6 2047.94
   671.8 2046.84   681.7 2049.55   835.4 2052.91   849.3 2055.69   908.5 2060.32
   954.2 2072.99  1065.2  2080.9  1089.6  2080.8  1117.5 2085.92  1148.4 2088.97
#Mann= 8 ,-1 , 0
       0      .1       0  118.81     .12       0  347.08      .1       0
   387.7    .045       0     437      .1       0  506.45     .12       0
  787.43     .06       0  923.11      .1       0
Bank Sta=387.7,437
XS Rating Curve= 0 ,0
Exp/Cntr=0.3,0.1

Type RM Length L Ch R = 1 ,3328    ,418.3,414,400
XS GIS Cut Line= 2
2218061.12809289356169.5777497292216951.40590289355820.966570318
#Sta/Elev= 30
       0  2137.1    77.4 2094.82    94.3 2087.97   142.7 2073.07   201.2  2057.6
   252.8 2048.52   280.3 2045.67   327.6 2045.02   428.2  2045.5     466 2046.78
   493.5 2044.44   514.1 2045.53     537 2044.41   548.5 2046.76   593.2 2046.33
   623.3  2041.8   651.7 2040.86   686.1 2043.94   720.5 2043.32   741.1 2041.03
   754.9 2041.69   759.4 2044.46   768.6 2048.15   790.8 2051.28   813.3  2050.8
   909.6 2062.24   947.4 2065.29  1104.8 2072.41  1135.1 2076.12  1163.2 2083.65
#Mann= 8 ,-1 , 0
       0      .1       0   99.97     .12       0  340.43      .1       0
  517.86     .12       0   720.5    .045       0   759.4     .06       0
  883.05     .12       0    1114      .1       0
Bank Sta=720.5,759.4
XS Rating Curve= 0 ,0
Exp/Cntr=0.3,0.1

Type RM Length L Ch R = 1 ,2914    ,470.2,477.5,485
XS GIS Cut Line= 2
 2218083.3501613355757.0779185592217279.18346256355530.688935637
#Sta/Elev= 30
       0 2147.92    58.9 2116.17    86.2 2098.23   104.4  2084.5   150.9 2046.03
   157.7 2042.86   171.4 2040.64   178.2 2042.16   191.8 2042.23   205.5 2039.88
     232 2042.73     260  2041.2   287.3 2042.15   303.8 2041.28   338.3 2042.75
   450.9 2044.23   464.5 2040.09   481.5 2036.94   539.5 2038.22   551.8 2040.52
   561.8 2042.33   575.1 2050.31   580.4 2052.15   596.4 2050.05   614.5 2049.79
   621.3 2050.69   631.5 2054.59   638.9 2055.14   662.2 2055.41   835.4 2065.66
#Mann= 7 ,-1 , 0
       0     .12       0  188.89      .1       0  252.81     .12       0
   464.5    .045       0   551.8     .12       0  552.17     .06       0
   695.7     .12       0
Bank Sta=464.5,551.8
XS Rating Curve= 0 ,0
Exp/Cntr=0.3,0.1

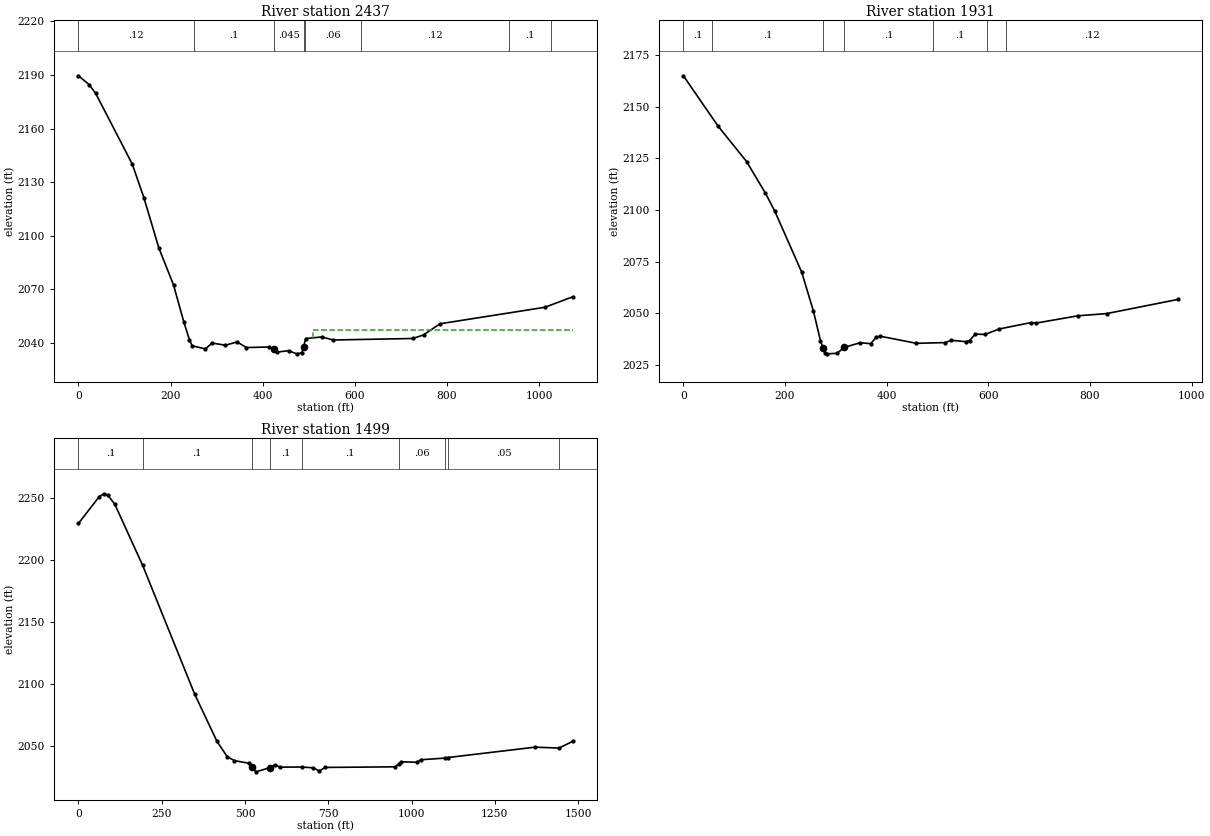
Type RM Length L Ch R = 1 ,2437    ,492.1,506,516.3
XS GIS Cut Line= 3
2218244.46138763355402.9109759782217775.01678847355187.633191317
2217262.51682922354970.966629893
#Sta/Elev= 30
       0 2189.49    23.1 2184.59    37.5  2179.6   116.9 2140.07     142 2121.37
   174.6 2093.17   206.4 2072.52   228.6 2051.98     241 2041.78   246.8 2038.52
   275.7 2036.75   290.1 2040.05     319 2038.83   344.3 2040.65   364.7 2037.53
   412.9 2037.85   423.7 2036.65   430.9 2034.97   456.3 2035.78   473.6 2034.01
     485 2034.61   488.7 2038.06   493.4 2042.54   528.2 2043.47   553.2 2041.75
     726 2042.59     749 2044.59   784.7 2050.81  1012.6 2060.05  1072.9 2065.91
#Mann= 8 ,-1 , 0
       0     .12       0  251.23      .1       0   423.7    .045       0
   488.7      .1       0  492.27     .06       0  612.34     .12       0
  933.77      .1       0 1026.84     .12       0
#XS Ineff= 2 , 0
                          508.66         2047.59
Permanent Ineff=
       F       F
Bank Sta=423.7,488.7
XS Rating Curve= 0 ,0
Exp/Cntr=0.3,0.1

Type RM Length L Ch R = 1 ,1931    ,439.1,432.2,415.9
XS GIS Cut Line= 4
2218426.40590563355095.9667079752218138.90582447354815.411166728
 2217886.1281148354691.7998653952217598.62803364354658.466598734
#Sta/Elev= 30
       0 2164.93      68 2140.64   124.3 2123.41   160.8 2108.37   179.3 2099.69
   232.7 2069.93   255.9 2050.98   269.7 2036.72   274.6 2033.33   279.1 2030.52
   283.5 2030.34   302.8 2030.62   316.2 2033.46   347.7 2035.69   368.5 2035.26
   379.8 2038.46   387.3 2038.87   458.5 2035.43   515.7 2035.79   526.7 2036.91
   555.9 2036.22   563.2 2036.79   574.1 2039.89   593.4 2039.73   621.6 2042.39
   683.6 2045.45   693.5  2045.2     776 2048.75     833 2049.83   972.5 2056.65
#Mann= 7 ,-1 , 0
       0      .1       0   55.76      .1       0   274.6    .045       0
   316.2      .1       0  490.29      .1       0  598.29     .06       0
  634.82     .12       0
Bank Sta=274.6,316.2
XS Rating Curve= 0 ,0
Exp/Cntr=0.3,0.1

Type RM Length L Ch R = 1 ,1499    ,621.7,624,609.3
XS GIS Cut Line= 3
2218947.23918155354920.9667298942218580.57259205354615.411238641
2217641.68339372 354252.91097939
#Sta/Elev= 30
       0 2229.18    62.3 2250.69    76.2 2253.03    87.8 2252.08   109.3 2244.53
   192.7 2195.49   348.7 2092.01   415.7 2053.95   446.4 2041.62     468 2038.42
   511.9 2036.26  520.872032.963     533 2029.38   575.8 2032.85   589.2 2034.85
   606.2 2033.15   670.1 2033.27   705.3  2032.6   722.9 2030.07   740.7 2032.92
   950.8 2033.42   961.4 2035.91     969  2037.5  1014.8 2037.09  1028.9 2039.12
  1099.2 2040.42  1108.6 2040.87  1370.1 2049.22  1442.6 2048.52  1483.7 2053.92
#Mann= 9 ,-1 , 0
       0      .1       0   192.7      .1       0  520.87    .045       0
   575.8      .1       0   670.1      .1       0   961.4     .06       0
  1099.2      .1       0  1108.6     .05       0  1442.6     .12       0
Bank Sta=520.87,575.8
XS Rating Curve= 0 ,0
Exp/Cntr=0.5,0.3