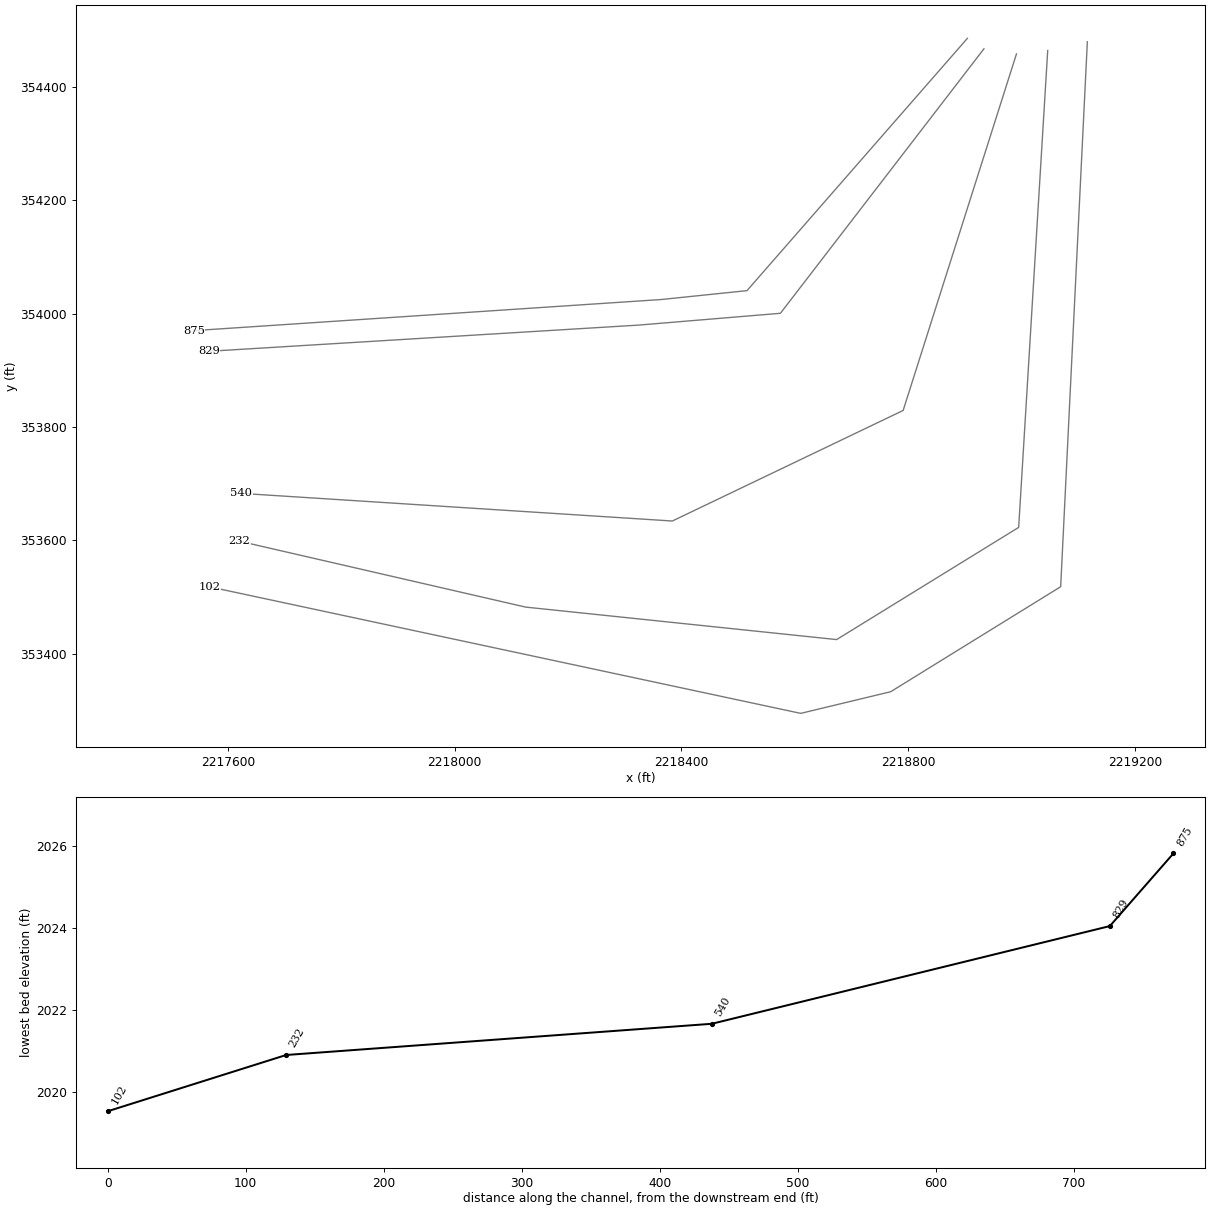
HEC-RAS study NFANTNYCK.prj: NFANTNYCK

--- NFANTNYCK.g01 (geometry) --- (continued)

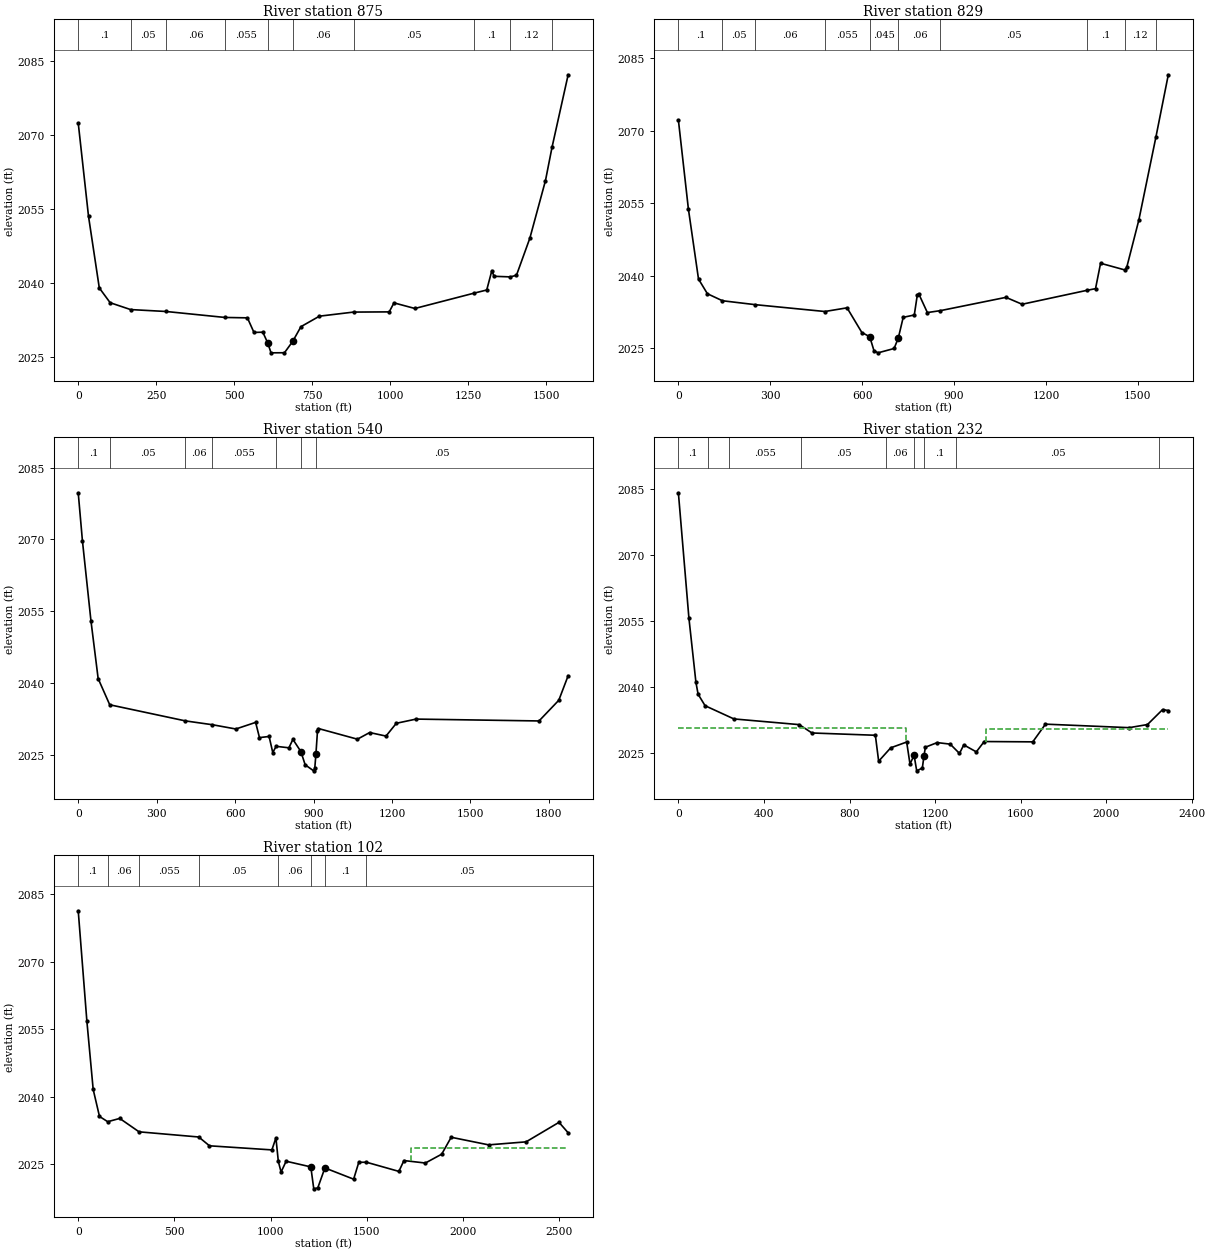
Type RM Length L Ch R = 1 ,875     ,57,46.1,48.2
XS GIS Cut Line= 4
2218904.68795149 354485.864630262218515.81550372354040.719146565
2218364.77381106354025.0941778122217539.99474054353970.201919098
#Sta/Elev= 30
       0 2072.46      33  2053.5    67.5 2038.98   102.3 2035.98   167.7 2034.59
   281.6  2034.2     470 2032.99     542 2032.91     563 2029.95   591.4    2030
  607.122027.812   617.7 2025.81   660.7 2025.83     687 2028.12   713.5 2031.12
   772.7 2033.25     882 2034.08   996.3 2034.12  1011.5 2035.95  1078.5 2034.81
  1267.4 2037.91  1308.7 2038.56  1325.1  2042.5  1332.1 2041.34  1384.5 2041.22
    1404 2041.56  1446.8 2049.07  1496.8 2060.74  1517.9 2067.53  1569.5 2082.23
#Mann= 10 ,-1 , 0
       0      .1       0   167.7     .05       0   281.6     .06       0
     470    .055       0  607.12    .045       0     687     .06       0
     882     .05       0  1267.4      .1       0  1384.5     .12       0
  1517.9      .1       0
#XS Ineff= 2 , 0
             594  2027.3     700          2027.3
Permanent Ineff=
       F       F
Bank Sta=607.12,687
XS Rating Curve= 0 ,0
Exp/Cntr=0.5,0.3

Type RM Length L Ch R = 1 ,829     ,268.5,288.5,300.7
XS GIS Cut Line= 4
2218933.91060921354467.4490733712218574.84327281354000.788780227
2218324.84344472353979.9554885632217566.47852015353933.743658681
#Sta/Elev= 30
       0 2072.26    32.6 2053.87    65.7 2039.32    94.7 2036.28   143.7 2034.83
   250.3 2034.02   478.2  2032.6   550.7 2033.36     599 2028.25   624.72027.382
   638.5  2024.5   651.7 2024.04   704.3 2024.94   718.12027.138     734 2031.39
   770.2 2031.88     780    2036   784.4  2036.3   812.9 2032.38   855.7 2032.78
  1069.4 2035.53  1122.2  2034.1  1332.8 2036.97  1361.9 2037.33  1378.4 2042.59
  1456.8 2041.22  1463.8 2041.74  1503.3 2051.54    1559 2068.71  1599.5 2081.62
#Mann= 10 ,-1 , 0
       0      .1       0   143.7     .05       0   250.3     .06       0
   478.2    .055       0   624.7    .045       0   718.1     .06       0
   855.7     .05       0  1332.8      .1       0  1456.8     .12       0
    1559      .1       0
Bank Sta=624.7,718.1
XS Rating Curve= 0 ,0
Exp/Cntr=0.5,0.3

Type RM Length L Ch R = 1 ,540     ,303.5,308.5,309.9
XS GIS Cut Line= 4
2218991.26083361354458.4031521152218791.33003659353829.352595654
2218384.15390121353634.2981595432217623.44160037353683.061768571
#Sta/Elev= 30
       0 2079.74      16 2069.75    48.6 2053.04    76.2 2040.93   120.5 2035.46
   410.1 2032.09   513.4 2031.29   602.9  2030.4   678.5 2031.78   693.2  2028.6
   730.1 2028.84     744 2025.49   757.1 2026.78   805.8 2026.47   821.1 2028.23
   851.62025.682     868 2022.92   900.4 2021.66   904.7 2022.17   909.2 2025.22
     915 2029.88   918.6  2030.5  1067.8 2028.27  1114.7 2029.66  1177.2 2028.92
  1216.6 2031.59  1292.2 2032.47  1762.4 2032.08    1838  2036.4  1873.8 2041.53
#Mann= 7 ,-1 , 0
       0      .1       0   120.5     .05       0   410.1     .06       0
   513.4    .055       0   757.1     .06       0   851.6    .045       0
   909.2     .05       0
Bank Sta=851.6,909.2
XS Rating Curve= 0 ,0
Exp/Cntr(USF)=0,0
Exp/Cntr=0.3,0.1

Type RM Length L Ch R = 1 ,232     ,130,129.3,128.6
XS GIS Cut Line= 5
2219046.38645275354464.4318390462218995.15575239353623.050034389
2218673.97529238353425.1334354732218125.36418489353482.424987555
2217620.15587772353598.744308725
#Sta/Elev= 30
       0 2084.21    49.2  2055.7      82 2041.05    92.2 2038.34   124.8 2035.73
   259.5 2032.72   565.2 2031.42   624.4 2029.52   920.8    2029   936.2 2023.09
   992.5 2026.14  1067.2 2027.46  1082.6 2022.47  1101.9 2024.43  1114.1  2020.9
  1140.4 2021.54  1148.1 2024.31  1154.6 2026.28  1209.8 2027.33  1270.7 2026.98
  1314.1 2024.86  1334.1 2026.81  1392.7 2025.22  1429.6 2027.57  1656.7  2027.5
    1716 2031.53  2107.4 2030.73  2192.9 2031.44  2263.6 2034.85  2290.2 2034.63
#Mann= 9 ,-1 , 0
       0      .1       0  136.64     .06       0  234.59    .055       0
  574.17     .05       0  969.37     .06       0  1101.9    .045       0
  1148.1      .1       0 1298.71     .05       0 2245.94      .1       0
#XS Ineff= 2 , 0
         1065.36 2030.73 1436.05         2030.46
Permanent Ineff=
       F       F
Bank Sta=1101.9,1148.1
XS Rating Curve= 0 ,0
Exp/Cntr=0.3,0.1

Type RM Length L Ch R = 1 ,102     ,,,
XS GIS Cut Line= 5
2219116.30549919354479.8266140452219069.26250649 353518.38545054
2218769.36342796353333.1536667452218610.59332756353294.931235169
2217566.82692682 353518.38545054
#Sta/Elev= 30
       0 2081.37    44.8  2056.9    77.7 2041.64   110.5 2035.63   153.2 2034.46
   215.7 2035.19   316.1 2032.21   626.2 2031.06   682.1  2029.1  1006.4 2028.19
  1027.3 2030.86  1039.8 2025.64  1054.1 2023.26  1080.3 2025.67  1208.6 2024.41
    1224 2019.53  1244.8 2019.74  1281.8 2024.18  1431.1 2021.68  1457.9 2025.43
  1497.5 2025.45  1666.2 2023.41  1692.5 2025.82  1803.8 2025.27  1888.7 2027.24
    1938    2031  2132.6 2029.31  2327.2 2029.98  2498.3 2034.32  2545.8    2032
#Mann= 8 ,-1 , 0
       0      .1       0   153.2     .06       0   316.1    .055       0
   626.2     .05       0  1039.8     .06       0  1208.6    .045       0
  1281.8      .1       0  1497.5     .05       0
#XS Ineff= 2 , 0
                         1726.66         2028.69
Permanent Ineff=
       F       F
Bank Sta=1208.6,1281.8
XS Rating Curve= 0 ,0
Exp/Cntr(USF)=0,0
Exp/Cntr=0.3,0.1
LCMann Table=0

Chan Stop Cuts=-1
Use User Specified Reach Order=0
Composite Channel Slope=5